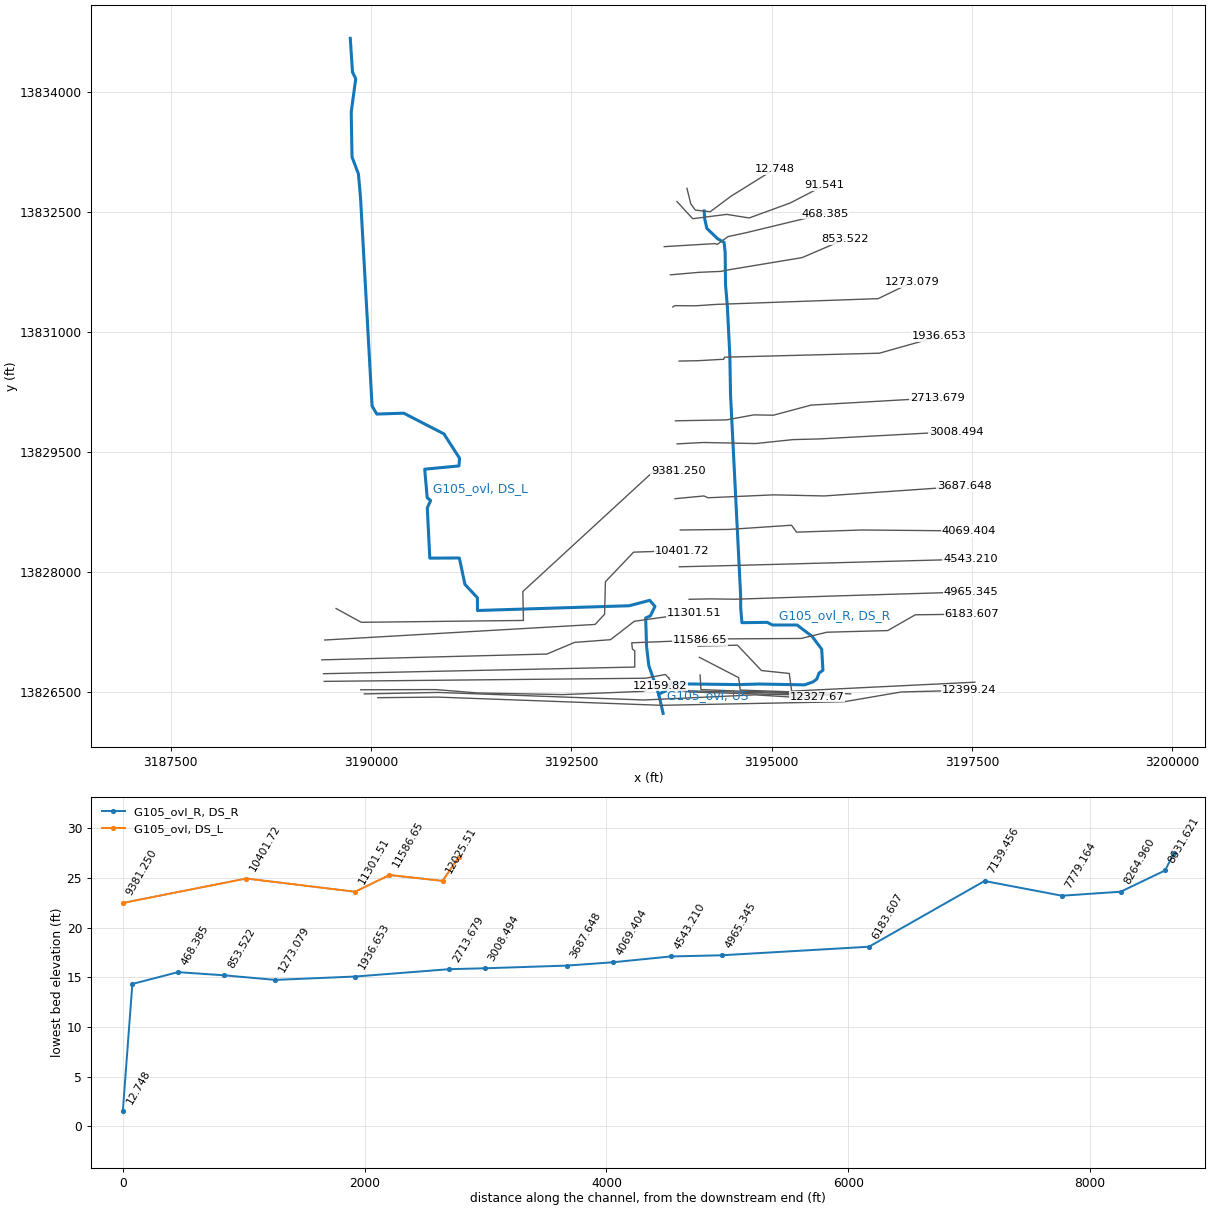
--- G105_ovrlnd.prj (project) ---

Proj Title=G105 overland flow
Current Plan=p01
Default Exp/Contr=.3,.1
English Units
Geom File=g04
Geom File=g02
Flow File=f02
Flow File=f01
Plan File=p01
Plan File=p04
Plan File=p03
Y Axis Title=Elevation
X Axis Title(PF)=Main Channel Distance
X Axis Title(XS)=Station
BEGIN DESCRIPTION:
END DESCRIPTION:
DSS Export Rating Curves= 0
DSS Export Rating Curve Sorted= 0
DSS Export Volume Flow Curves= 0
DXF OffsetX= 0
DXF OffsetY= 0
DXF ScaleX= 1
DXF ScaleY= 10

--- G105_ovrlnd.p01 (plan) ---

Plan Title=DS Rating - with downstream model
Program Version=3.11
Short Identifier=Rating w DS
Geom File=g04
Flow File=f02
Subcritical Flow
K Sum by GR= 0
Std Step Tol= 0.01
Critical Tol= 0.01
Num of Std Step Trials= 20
Max Error Tol= 0.3
Flow Tol Ratio= 0.001
Split Flow NTrial= 30
Split Flow Tol= 0.02
Split Flow Ratio= 0.02
Log Output Level= 0
Friction Slope Method= 0
Unsteady Friction Slope Method= 2
Unsteady Bridges Friction Slope Method= 1
Secant Critical Depth
Global Vel Dist= 0 , 0 , 0
Global Log Level= 0
CheckData=True
Encroach Param=-1 ,0,0, 0
Optimized Junction=1
Computation Interval=1HOUR
Output Interval=1HOUR
Run HTab= 0
Run UNet= 0
Run PostProcess= 0
UNET Theta= 1
UNET Theta Warmup= 1
UNET ZTol= 0.02
UNET ZSATol= 0.05
UNET MxIter= 20
UNET MaxInSteps= 0
UNET DtIC= 0
UNET DtMin= 0
UNET MaxCRTS= 20
UNET WFStab= 2
UNET SFStab= 1
UNET WFX= 1
UNET SFX= 1
UNET DSS MLevel= 4
UNET DZMax Abort= 100
UNET Convert EG Bridges=-1
UNET Use Existing IB Tables=-1
UNET Froude Reduction=False
UNET Froude Limit= 1
UNET Froude Power= 10
Instantaneous Interval=1HOUR
Write IC File= 0
Echo Input=False
Echo Output=False
Write Detailed= 0
Detailed Automatic Start=False, 10

--- G105_ovrlnd.p03 (plan) ---

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Plan Title=DS Rating - no downstream model
Short Identifier=Rating no DS
Geom File=g02
Flow File=f02

--- G105_ovrlnd.p04 (plan) ---

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Plan Title=Flood Hazard DS
Short Identifier=FH Qs
Geom File=g04
Flow File=f01

--- G105_ovrlnd.f02 (steady flow) ---

Flow Title=0.1 - 2,500 cfs
Program Version=3.11
Number of Profiles= 15
Profile Names=PF 1,PF 2,PF 3,PF 4,PF 5,PF 6,PF 7,PF 8,PF 9,PF 10,PF 11,PF 12,PF 13,PF 14,PF 15
River Rch & RM=G105_ovl,US              ,12399.24
      .1       5      10      25      50     100     150     200     300     500
     750    1000    1500    2000    2500
River Rch & RM=G105_ovl,DS_L            ,12159.82
      .1    3.33     5.8   11.55   23.49   47.17   70.56   93.61  132.68  241.63
  381.56  530.65  856.12 1221.12 1596.78
River Rch & RM=G105_ovl_R,DS_R            ,8705.345
     .01    1.67     4.2   13.45   26.51   52.83   79.44  106.39  167.32  258.37
  368.44  469.35  643.88  778.88  903.22
Boundary for River Rch & Prof#=G105_ovl,DS_L            , 1
Up Type= 0
Dn Type= 3
Dn Slope=0.02
Boundary for River Rch & Prof#=G105_ovl,DS_L            , 2
Up Type= 0
Dn Type= 3
Dn Slope=0.02
Boundary for River Rch & Prof#=G105_ovl,DS_L            , 3
Up Type= 0
Dn Type= 3
Dn Slope=0.02
Boundary for River Rch & Prof#=G105_ovl,DS_L            , 4
Up Type= 0
Dn Type= 3
Dn Slope=0.02
Boundary for River Rch & Prof#=G105_ovl,US              , 1
Up Type= 2
Dn Type= 0
Boundary for River Rch & Prof#=G105_ovl,US              , 2
Up Type= 2
Dn Type= 0
Boundary for River Rch & Prof#=G105_ovl,US              , 3
Up Type= 2
Dn Type= 0
Boundary for River Rch & Prof#=G105_ovl,US              , 4
Up Type= 2
Dn Type= 0
Boundary for River Rch & Prof#=G105_ovl_R,DS_R            , 1
Up Type= 0
Dn Type= 3
Dn Slope=0.02
Boundary for River Rch & Prof#=G105_ovl_R,DS_R            , 2
Up Type= 0
Dn Type= 3
Dn Slope=0.02
Boundary for River Rch & Prof#=G105_ovl_R,DS_R            , 3
Up Type= 0
Dn Type= 3
Dn Slope=0.02
Boundary for River Rch & Prof#=G105_ovl_R,DS_R            , 4
Up Type= 0
Dn Type= 3
Dn Slope=0.02
DSS Import GetInterval= 0
DSS Import GetPeak= 0
DSS Import FillOption= 0

--- G105_ovrlnd.f01 (steady flow) ---

Flow Title=Flood Hazard discharges
Program Version=3.11
Number of Profiles= 4
Profile Names=10%,2%,1%,0.2%
River Rch & RM=G105_ovl,US              ,12399.24
      44     509     774    1733
River Rch & RM=G105_ovl,DS_L            ,12159.82
      22     254     387     866
River Rch & RM=G105_ovl_R,DS_R            ,8705.345
      22     255     387     867
Boundary for River Rch & Prof#=G105_ovl,DS_L            , 1
Up Type= 0
Dn Type= 3
Dn Slope=0.02
Boundary for River Rch & Prof#=G105_ovl,DS_L            , 2
Up Type= 0
Dn Type= 3
Dn Slope=0.02
Boundary for River Rch & Prof#=G105_ovl,DS_L            , 3
Up Type= 0
Dn Type= 3
Dn Slope=0.02
Boundary for River Rch & Prof#=G105_ovl,DS_L            , 4
Up Type= 0
Dn Type= 3
Dn Slope=0.02
Boundary for River Rch & Prof#=G105_ovl,US              , 1
Up Type= 2
Dn Type= 0
Boundary for River Rch & Prof#=G105_ovl,US              , 2
Up Type= 2
Dn Type= 0
Boundary for River Rch & Prof#=G105_ovl,US              , 3
Up Type= 2
Dn Type= 0
Boundary for River Rch & Prof#=G105_ovl,US              , 4
Up Type= 2
Dn Type= 0
Boundary for River Rch & Prof#=G105_ovl_R,DS_R            , 1
Up Type= 0
Dn Type= 3
Dn Slope=0.02
Boundary for River Rch & Prof#=G105_ovl_R,DS_R            , 2
Up Type= 0
Dn Type= 3
Dn Slope=0.02
Boundary for River Rch & Prof#=G105_ovl_R,DS_R            , 3
Up Type= 0
Dn Type= 3
Dn Slope=0.02
Boundary for River Rch & Prof#=G105_ovl_R,DS_R            , 4
Up Type= 0
Dn Type= 3
Dn Slope=0.02
DSS Import GetInterval= 0
DSS Import GetPeak= 0
DSS Import FillOption= 0

--- G105_ovrlnd.g04 (geometry) ---

Geom Title=Split Flow - Downstream Model
Program Version=3.11

Junct Name=1
Junct Desc=underpass split, 0 , 0 ,-1
Up River,Reach=G105_ovl        ,US
Dn River,Reach=G105_ovl        ,DS_L
Dn River,Reach=G105_ovl_R      ,DS_R
Junc L&A=168,10
Junc L&A=221,80

River Reach=G105_ovl        ,US
Reach XY= 30
      3193647.38    13826236.796       3193647.2    13826237.582
      3193645.47    13826245.156     3193644.384    13826249.913
     3193642.045    13826260.156     3193639.626    13826270.745
     3193638.806    13826274.336     3193638.619    13826275.156
     3193636.017    13826286.547     3193635.193    13826290.156
     3193633.881    13826295.901     3193631.767    13826305.156
     3193630.439    13826310.969     3193625.001    13826334.781
     3193624.915    13826335.156     3193624.626    13826336.422
     3193622.073    13826347.602      3193621.49    13826350.156
     3193620.561    13826354.221     3193618.064    13826365.156
     3193616.495    13826372.025     3193614.638    13826380.156
     3193611.682      13826393.1     3193611.212    13826395.156
     3193610.567    13826397.979     3193604.469    13826424.683
     3193594.626    13826467.778     3193594.184    13826469.714
     3193593.922     13826470.86     3193592.238    13826478.234

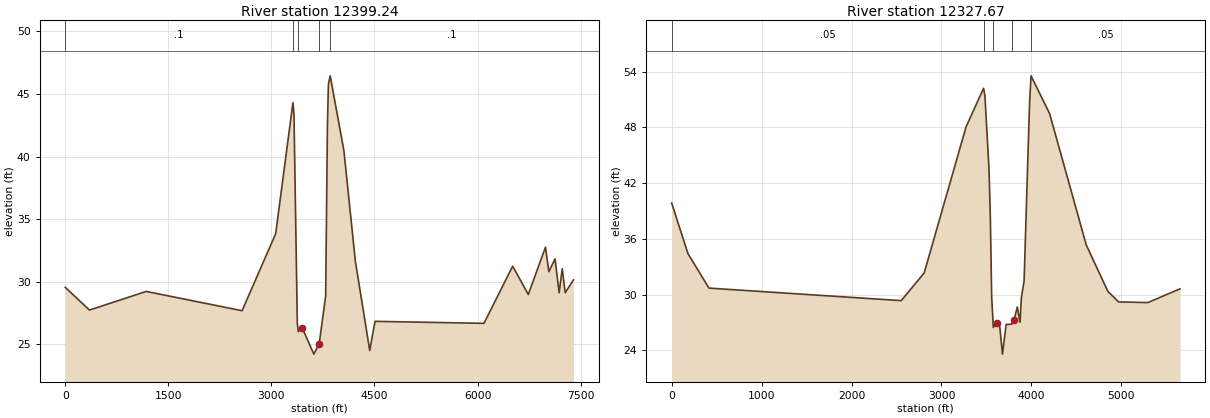
Type RM Length L Ch R = 1 ,12399.24,68,71.57,78.15
XS GIS Cut Line= 6
     3190087.365    13826432.931     3190838.592    13826440.086
     3193625.286    13826337.649     3195911.162     13826382.85
     3196619.461    13826504.477     3197463.697    13826525.941
#Sta/Elev= 30
       0   29.55  353.42   27.73 1178.24   29.22 2573.73   27.68 3062.76   33.83
 3313.89    44.3 3329.15   43.33 3377.68   26.64 3392.69      26 3448.22   26.32
 3617.93   24.21 3695.73   25.03 3790.13   28.86 3815.92   42.51 3830.07   45.78
 3855.81   46.45 4055.27   40.48 4222.11   31.64 4431.38    24.5 4508.15   26.83
 6093.72   26.67 6511.57   31.24 6738.82   28.98 6989.05   32.76  7037.8    30.8
 7127.81   31.82 7187.82   29.12 7232.83   31.03 7275.75   29.12 7396.92   30.14
#Mann= 5 ,-1 , 0
       0      .1       0 3313.89     .04       0 3392.69     .02       0
 3695.73     .04       0 3855.81      .1       0
Bank Sta=3448.22,3695.73
XS Rating Curve= 0
Exp/Cntr=0.3,0.1

Type RM Length L Ch R = 1 ,12327.67,,,
XS GIS Cut Line= 6
     3189918.691    13826479.874     3190841.067    13826498.549
     3193405.393    13826404.118     3194795.937    13826468.423
     3195372.299    13826432.587     3195563.424    13826444.533
#Sta/Elev= 30
       0   39.86  181.04   34.41  414.72    30.7 2552.34   29.35 2808.13   32.33
  3273.3   48.05 3468.56   52.22 3483.58   51.37 3528.59   43.56 3543.59   38.37
  3558.6   29.72 3576.67   26.46 3614.17   26.97 3648.61   26.53 3678.61   23.59
 3719.37   26.79 3783.62   26.82 3808.85    27.3 3843.62   28.67 3873.62   27.02
 3888.72   29.66 3919.04   31.47 3979.66   50.58 3996.24   53.56 4202.15   49.51
 4610.14   35.35 4850.91   30.34 4970.35   29.21 5295.07   29.14  5652.7   30.62
#Mann= 5 ,-1 , 0
       0     .05       0 3468.56     .04       0 3576.67     .02       0
 3783.62     .04       0 3996.24     .05       0
Bank Sta=3614.17,3808.85
XS Rating Curve= 0
Exp/Cntr=0.3,0.1

River Reach=G105_ovl_R      ,DS_R
Reach XY= 30
     3193592.238    13826478.234     3193678.128    13826516.506
     3193744.642    13826619.115     3193759.616    13826623.022
     3193888.079    13826605.584     3194591.967    13826596.618
     3194848.375    13826603.707     3195412.611    13826593.291
      3195520.25    13826631.485     3195565.388    13826666.207
     3195593.166     13826740.86     3195641.777    13826775.582
     3195626.152    13827039.471     3195506.361    13827199.194
     3195318.861    13827341.555     3195011.569    13827341.555
     3194945.597    13827374.541      3194630.71    13827370.418
     3194615.736    13827555.964     3194614.383    13827717.459
     3194488.849    13830214.692     3194479.883    13830707.862
     3194448.499     13831331.05     3194426.082    13831595.568
     3194421.599    13831994.588     3194408.149    13832124.605
     3194327.448    13832169.439     3194192.947    13832299.456
     3194166.224    13832419.711     3194159.922    13832517.498

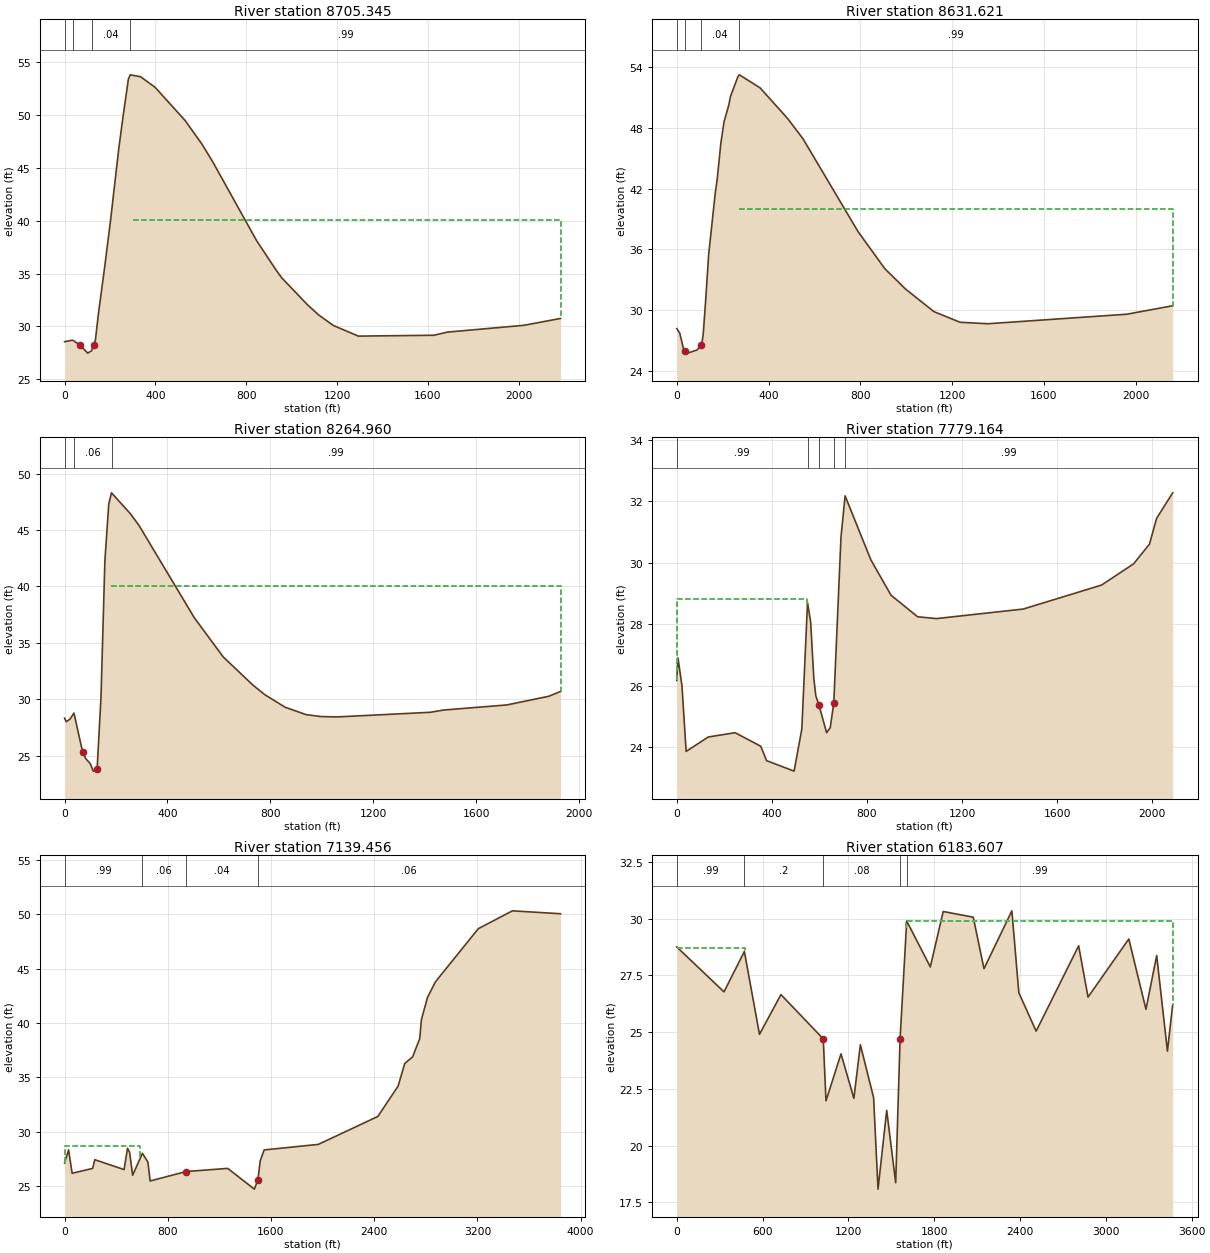
Type RM Length L Ch R = 1 ,8705.345,106.06,73.72,52.42
XS GIS Cut Line= 6
     3193604.848    13826582.212      3193649.59    13826591.772
     3193742.038    13826544.897     3193987.693    13826503.603
     3195004.098    13826474.306     3195772.466    13826459.464
#Sta/Elev= 30
       0   28.56   35.56   28.71   68.42   28.23  101.85   27.48  118.67    27.7
  127.73   28.28  135.49   28.67  148.83   31.18  177.47   35.78  203.51   40.24
  238.33   46.78   258.5   50.03  280.86   53.39  288.92   53.81  334.55   53.63
  398.51   52.63  530.32    49.5  604.28   47.27  650.54   45.65  845.62   38.12
   932.6    35.3  956.46    34.6 1069.82   32.05 1118.91   31.09 1183.88   30.09
  1293.9   29.09 1625.94   29.17 1686.46   29.47    2022   30.11 2183.84   30.76
#Mann= 4 ,-1 , 0
       0     .02       0   35.56    .015       0  118.67     .04       0
  288.92     .99       0
#XS Ineff= 2 , 0
                          300.82           40.04
Permanent Ineff=
       F       F
Bank Sta=68.42,127.73
XS Rating Curve= 0
Exp/Cntr=0.3,0.1

Type RM Length L Ch R = 1 ,8631.621,383.01,366.66,343.72
XS GIS Cut Line= 4
     3193718.926    13826676.585     3193786.559    13826555.027
     3193981.195    13826518.223     3195805.316     13826471.41
#Sta/Elev= 30
       0   28.18   13.08   27.73   30.24    26.1      36   25.96   47.41   25.76
   88.32   26.07  106.34   26.54  109.03   26.61  115.53   27.69  126.56   31.16
  139.11   35.51  168.22   41.65  175.86   42.84  192.23   46.49  205.87   48.58
  227.21   50.29  233.82   51.09  266.72   53.06  272.97   53.24  362.86   51.96
  482.84   48.94  550.69   46.91  790.77   37.74  906.96    34.1  996.61    32.1
 1120.88   29.86 1234.66   28.81 1355.47   28.66  1961.6    29.6 2161.91   30.44
#Mann= 4 ,-1 , 0
       0     .04       0      36     .03       0  106.34     .04       0
  272.97     .99       0
#XS Ineff= 2 , 0
                          271.19           40.04
Permanent Ineff=
       F       F
Bank Sta=36,106.34
XS Rating Curve= 0
Exp/Cntr=0.3,0.1

Type RM Length L Ch R = 1 ,8264.960,481.8,485.8,488.63
XS GIS Cut Line= 4
     3194108.791    13826716.555     3194119.272    13826534.467
     3194601.728    13826514.974      3195863.91    13826475.988
#Sta/Elev= 30
       0   28.32    6.41      28   21.43   28.24   36.46   28.77   66.51   25.68
   73.07   25.28   81.53   24.75   99.87   24.29  111.58   23.62  125.01   23.82
  126.61   23.85  141.63   30.23  156.66   42.28  171.68   47.31  182.39   48.31
  256.48   46.44  289.18   45.42  504.32   37.23   616.3   33.76  731.79   31.26
  778.52    30.4  857.39   29.29  939.18   28.63  997.37   28.46 1060.17   28.43
 1422.04   28.84 1473.52   29.04 1718.88   29.49 1882.34   30.26 1928.02   30.69
#Mann= 3 ,-1 , 0
       0      .5       0   36.46     .06       0  182.39     .99       0
#XS Ineff= 2 , 0
                          180.49              40
Permanent Ineff=
       F       F
Bank Sta=73.07,125.01
XS Rating Curve= 0
Exp/Cntr=0.3,0.1

Type RM Length L Ch R = 1 ,7779.164,298.34,639.71,641.49
XS GIS Cut Line= 4
     3194100.123    13826937.277     3194589.694    13826683.569
      3194609.85    13826527.969     3195987.367    13826480.861
#Sta/Elev= 30
       0   26.17    5.07    26.9   21.97   25.99   39.44   23.86  132.45   24.33
  245.42   24.47  353.27   24.03  378.16   23.56  493.62   23.22  526.22   24.59
  550.18    28.7  563.32   28.07  576.71   26.23   585.1   25.67  598.65   25.36
  630.47   24.47   645.6   24.63  660.69   25.44  690.97   30.83  708.31   32.17
  816.67   30.09   901.6   28.94 1013.26   28.24 1092.13   28.18 1457.37   28.49
  1787.2   29.27 1921.96   29.96 1988.83    30.6 2018.85   31.44 2086.63   32.27
#Mann= 5 ,-1 , 0
       0     .99       0  550.18     .06       0  598.65     .04       0
  660.69     .06       0  708.31     .99       0
#XS Ineff= 2 , 0
          549.95   28.81  712.65           30.55
Permanent Ineff=
       F       F
Bank Sta=598.65,660.69
XS Rating Curve= 0
Exp/Cntr=0.3,0.1

Type RM Length L Ch R = 1 ,7139.456,283.34,955.85,1053.41
XS GIS Cut Line= 6
     3194082.205    13827077.634     3194574.949    13827089.579
     3194874.416     13826772.11     3195221.638    13826735.652
       3195251.5    13826514.974     3197537.386    13826626.699
#Sta/Elev= 30
       0    27.1   30.65   28.31   58.54   26.16  217.48   26.61  234.33   27.41
  461.21    26.5  487.56   28.47  503.86   28.09  527.51   25.98  602.93      28
  645.52    27.2  663.19   25.45  941.44   26.32  1264.5   26.61 1470.97    24.7
 1498.17   25.54 1516.38   27.31 1546.84   28.31 1966.88   28.82 2427.88   31.39
 2584.82   34.18 2636.46   36.27 2697.65   36.88 2752.53   38.56 2766.03   40.32
 2812.51   42.34 2873.72   43.78 3207.03   48.69 3471.21   50.33 3844.04   50.06
#Mann= 4 ,-1 , 0
       0     .99       0  602.93     .06       0  941.44     .04       0
 1498.17     .06       0
#XS Ineff= 2 , 0
          586.62   28.64
Permanent Ineff=
       F       F
Bank Sta=941.44,1498.17
XS Rating Curve= 0
Exp/Cntr=0.3,0.1

Type RM Length L Ch R = 1 ,6183.607,519.73,1218.26,1124.95
XS GIS Cut Line= 6
     3194101.847    13827166.207     3195369.208    13827173.152
     3195690.391    13827251.189     3196450.363    13827271.745
      3196793.79    13827468.843      3197501.55    13827477.802
#Sta/Elev= 30
       0   28.75  330.26   26.77  472.65   28.55  578.36    24.9  728.36   26.65
 1024.21    24.7 1043.36   21.97 1148.36   24.04 1238.36   22.08 1283.67   24.44
 1376.29   22.11 1407.16   18.08  1467.9   21.55 1530.65   18.36 1561.26   24.68
 1607.71   29.89 1772.82   27.87 1862.89   30.31 2072.97   30.06 2147.98   27.79
 2343.02   30.34 2391.73   26.73 2512.79   25.04 2809.88    28.8 2875.57   26.54
 3160.59    29.1  3280.6      26 3355.61   28.37 3430.61   24.16 3467.54   26.21
#Mann= 5 ,-1 , 0
       0     .99       0  472.65      .2       0 1024.21     .08       0
 1561.26     .06       0 1607.71     .99       0
#XS Ineff= 2 , 0
          474.79   28.69 1604.83            29.9
Permanent Ineff=
       F       F
Bank Sta=1024.21,1561.26
XS Rating Curve= 0
Exp/Cntr=0.3,0.1

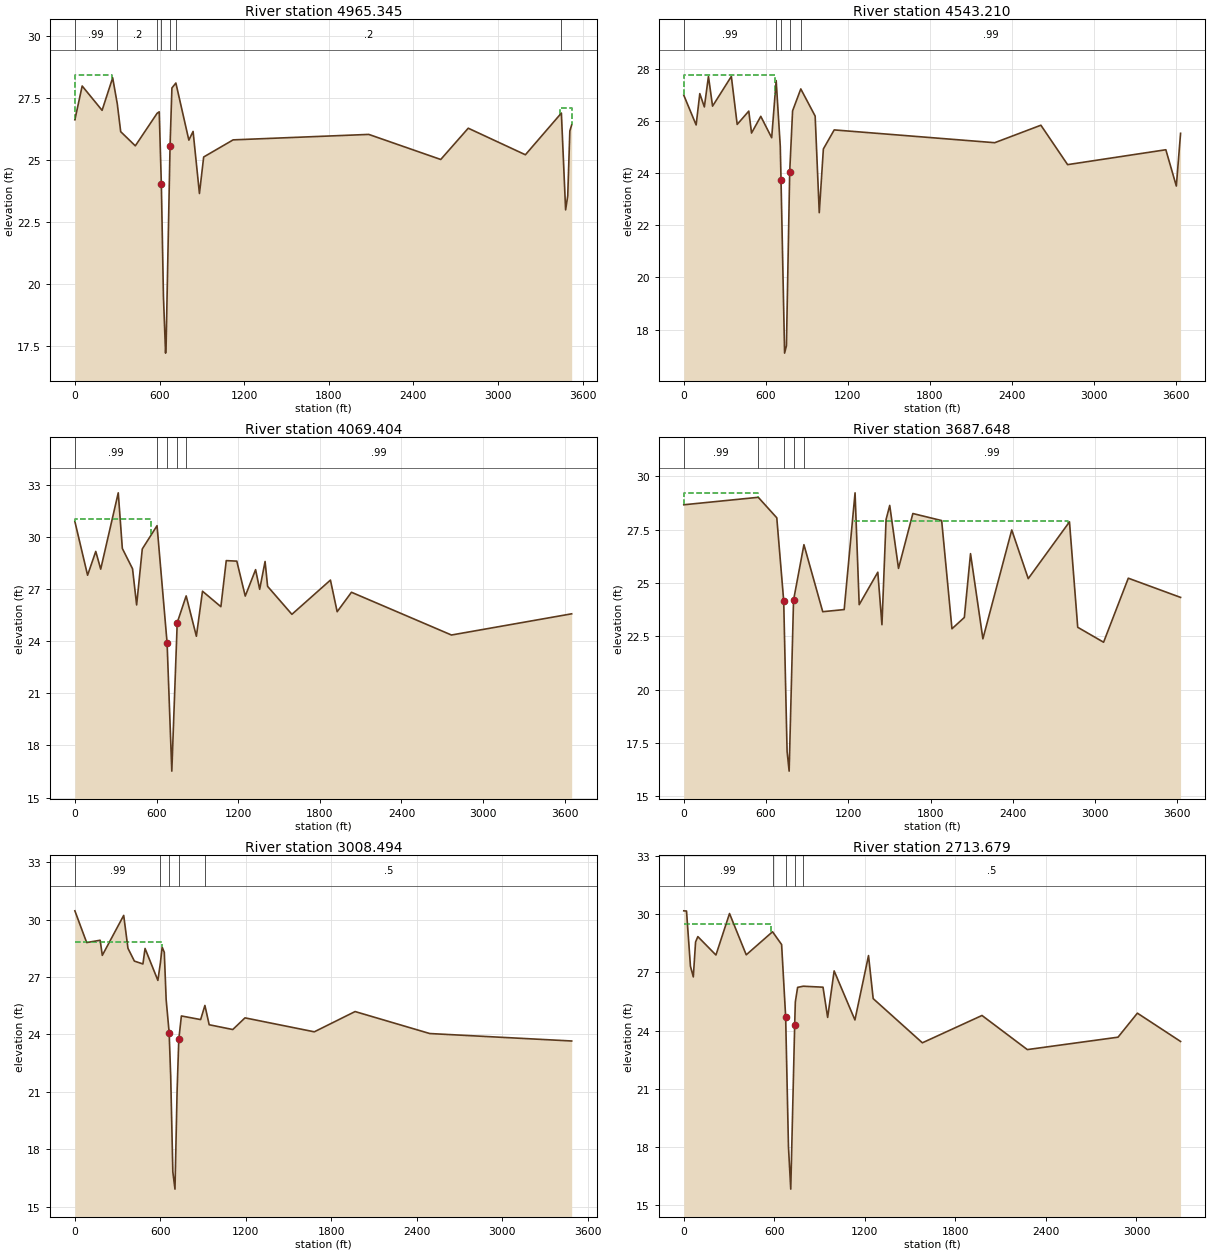
Type RM Length L Ch R = 1 ,4965.345,422.85,422.14,420.86
XS GIS Cut Line= 5
     3193971.711    13827662.954     3194232.055    13827667.944
     3194551.616    13827663.658     3195685.689    13827701.086
     3197492.591     13827755.53
#Sta/Elev= 30
       0   26.62   51.71   27.98  192.95      27  267.96   28.31  300.72   27.26
  324.89   26.14  428.51   25.57  582.99   26.88     598   26.94  613.01   24.04
  628.02   19.49  643.03   17.22  647.31   17.67  674.89   25.57  688.05    27.9
  716.06    28.1  808.12    25.8  838.13   26.15  883.16   23.65  913.17   25.12
 1122.08   25.81 2083.78   26.03 2594.01   25.02  2789.1   26.28 3194.28   25.21
  3449.4   26.89 3479.41   22.99 3494.42   23.55 3509.42   26.17 3522.39   26.41
#Mann= 7 ,-1 , 0
       0     .99       0  300.72      .2       0  582.99     .06       0
  613.01     .04       0  674.89     .06       0  716.06      .2       0
  3449.4     .99       0
#XS Ineff= 2 , 0
          260.31   28.43 3439.05           27.08
Permanent Ineff=
       F       F
Bank Sta=613.01,674.89
XS Rating Curve= 0
Exp/Cntr=0.3,0.1

Type RM Length L Ch R = 1 ,4543.210,466.73,473.81,481.12
XS GIS Cut Line= 3
     3193849.272    13828069.095     3194515.749    13828085.094
     3197480.646    13828164.657
#Sta/Elev= 30
       0   26.98   90.38   25.84  117.14   27.04   150.4   26.53  180.41    27.7
  210.41   26.56  347.74    27.7  390.47   25.86  475.15   26.37   495.5   25.53
  563.06   26.17  642.72   25.35  675.55   27.54  705.56   25.02  711.02   23.74
  737.16    17.1  750.58   17.38  774.59   24.05  795.59   26.38  855.62   27.22
  960.65   26.18  990.66   22.48 1020.67   24.92 1099.92   25.65 2273.81   25.16
 2611.25   25.83 2806.63   24.32 3524.88   24.89  3601.6    23.5 3632.63   25.52
#Mann= 5 ,-1 , 0
       0     .99       0  675.55     .06       0  711.02     .04       0
  774.59     .06       0  855.62     .99       0
#XS Ineff= 2 , 0
       0  667.28   27.76               0
Permanent Ineff=
       F       F
Bank Sta=711.02,774.59
XS Rating Curve= 0
Exp/Cntr=0.3,0.1

Type RM Length L Ch R = 1 ,4069.404,387.51,381.76,379.55
XS GIS Cut Line= 6
     3193861.217    13828528.989     3194469.902    13828535.999
     3195249.859    13828588.716     3195312.572    13828502.112
     3196124.853    13828528.989     3197462.728    13828517.044
#Sta/Elev= 30
       0   30.88   93.42   27.79  153.42   29.16  189.76   28.14   318.8   32.53
   348.8   29.33   423.8   28.16   453.8   26.08   495.3    29.3  603.81   30.64
  677.65    23.9  712.31   16.52  752.13   25.06  817.83    26.6  892.87   24.28
  937.89   26.87 1072.96   25.98 1112.52   28.63 1190.05    28.6 1252.07   26.59
 1328.09   28.11 1358.11   26.98 1397.76   28.58 1416.27   27.15 1594.93   25.54
 1878.09   27.51 1927.57   25.69 2032.63   26.81 2767.58   24.35 3650.94   25.57
#Mann= 5 ,-1 , 0
       0     .99       0  603.81     .06       0  677.65     .04       0
  752.13     .06       0  817.83     .99       0
#XS Ineff= 2 , 0
          557.29   31.02
Permanent Ineff=
       F       F
Bank Sta=677.65,752.13
XS Rating Curve= 0
Exp/Cntr=0.3,0.1

Type RM Length L Ch R = 1 ,3687.648,683.64,679.16,670.89
XS GIS Cut Line= 6
     3193795.518    13828920.198     3194155.666    13828954.402
     3194209.486    13828931.832     3195026.853    13828968.317
     3195658.955    13828954.484     3197403.001    13829075.487
#Sta/Elev= 30
       0   28.66  543.31   29.01  678.34   28.05  728.82   24.16  753.45   17.11
  768.47   16.18  800.57   24.19  876.39   26.79 1013.44   23.65 1169.94   23.75
 1249.26   29.22 1279.42   23.98 1415.17    25.5 1445.33   23.04  1475.5   27.97
 1502.07   28.63 1566.15   25.68 1670.83   28.25  1880.9   27.92    1956   22.85
  2046.3   23.38 2091.41   26.37 2181.62   22.38 2392.13   27.48 2512.41    25.2
 2813.14   27.86 2873.28   22.92 3061.97   22.22 3242.19   25.22 3623.46   24.32
#Mann= 5 ,-1 , 0
       0     .99       0  543.31     .06       0  728.82     .04       0
  800.57     .06       0  876.39     .99       0
#XS Ineff= 2 ,-1
       0  538.96   29.19 1239.23 2804.77   27.89
Permanent Ineff=
       F       F
Bank Sta=728.82,800.57
XS Rating Curve= 0
Exp/Cntr=0.3,0.1

Type RM Length L Ch R = 1 ,3008.494,287.99,294.82,355.33
XS GIS Cut Line= 6
     3193822.333    13829605.444     3194152.597    13829622.888
     3194798.201    13829609.438     3195268.955    13829658.755
     3195596.261    13829667.257     3197304.452    13829759.356
#Sta/Elev= 30
       0   30.47   82.76   28.81  177.54   28.93  192.56   28.14  342.75   30.23
  372.75   28.51  417.75   27.84  477.75   27.69  492.75    28.5  582.75   26.83
  600.49   27.75  612.75   28.57  627.76    28.3  640.91   25.82  661.89    24.1
  672.79    21.8   687.8   16.81  702.81   15.91  717.82   21.07  729.66   23.75
  747.84   24.97  882.94   24.78  912.96   25.52  942.98   24.51 1108.63   24.26
 1194.47   24.87  1681.1   24.14 1967.35    25.2 2491.77   24.05 3488.04   23.66
#Mann= 5 ,-1 , 0
       0     .99       0  600.49     .06       0  661.89     .04       0
  729.66     .06       0  912.96      .5       0
#XS Ineff= 2 , 0
          612.74   28.84
Permanent Ineff=
       F       F
Bank Sta=661.89,729.66
XS Rating Curve= 0
Exp/Cntr=0.3,0.1

Type RM Length L Ch R = 1 ,2713.679,780.75,777.03,786.74
XS GIS Cut Line= 6
      3193801.49    13829893.741     3194439.532     13829905.34
     3194780.268    13829968.107      3195022.37    13829963.624
     3195494.163    13830089.997     3197068.533    13830180.428
#Sta/Elev= 30
       0   30.18   18.14   30.17   44.16   27.32   63.14   26.77   78.14   28.57
   93.14   28.85  213.14    27.9  303.15   30.04   413.9   27.91  588.25    29.1
  648.37   28.44  675.08   24.72  693.83   17.99  708.98   15.82  734.96   24.28
  739.28   25.48  754.43   26.23  791.71   26.29  922.79   26.24  953.51   24.68
   996.5   27.08 1134.26   24.55 1224.28   27.87 1255.24   25.65 1581.15   23.37
 1976.34   24.78 2276.83   23.02 2877.82   23.66 3006.26    24.9 3292.41   23.44
#Mann= 5 ,-1 , 0
       0     .99       0  588.25     .06       0  675.08     .04       0
  734.96     .06       0  791.71      .5       0
#XS Ineff= 2 , 0
          580.66   29.48
Permanent Ineff=
       F       F
Bank Sta=675.08,734.96
XS Rating Curve= 0
Exp/Cntr=0.3,0.1

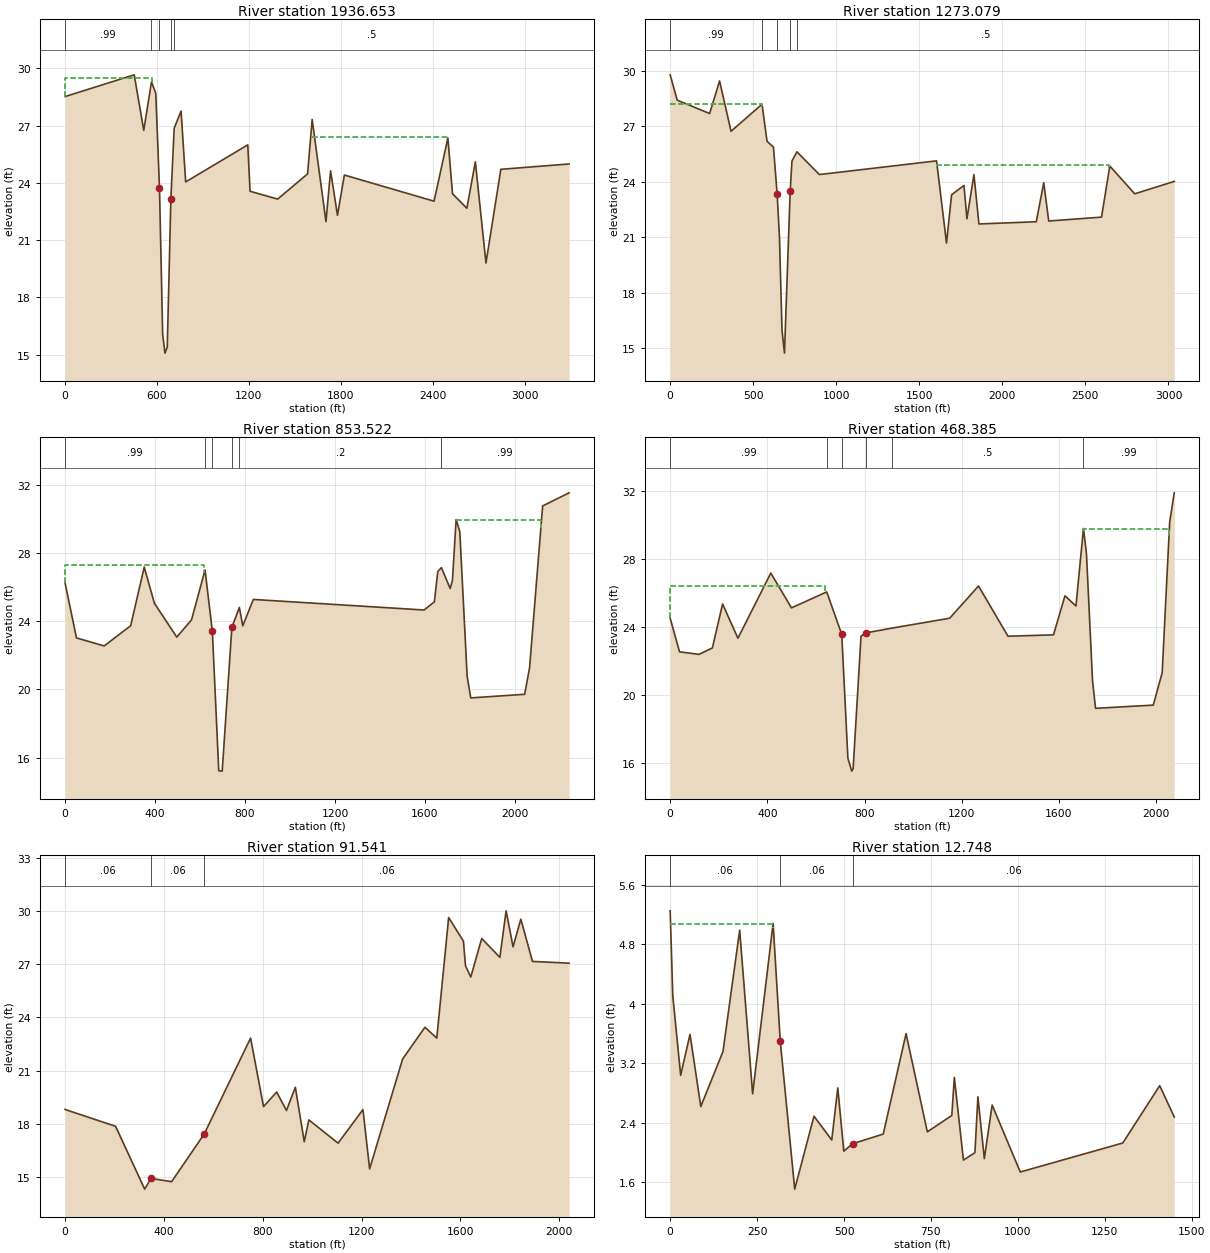
Type RM Length L Ch R = 1 ,1936.653,663.59,663.57,665.47
XS GIS Cut Line= 6
     3193846.285    13830640.323     3194080.863    13830645.095
     3194403.665    13830663.029     3194412.611    13830688.777
     3196345.841    13830738.872     3197086.451    13830947.914
#Sta/Elev= 30
       0   28.52  451.67   29.66  513.82   26.75  564.28   29.29   592.2   28.69
  616.45   23.73  637.23   16.05  652.24   15.08  667.24    15.4  690.87   23.18
  712.27   26.86  757.29   27.76   787.3   24.05 1192.43   25.99 1207.44   23.56
 1387.49   23.15 1582.56   24.47 1612.56   27.32 1702.59   21.97  1732.6   24.63
 1777.62    22.3 1822.63   24.41 2407.82   23.04 2497.85   26.35  2528.2   23.43
 2621.71   22.67 2677.14    25.1  2746.4    19.8 2843.47   24.71 3288.61   24.99
#Mann= 5 ,-1 , 0
       0     .99       0  564.28     .06       0  616.45     .04       0
  690.87     .06       0  712.27      .5       0
#XS Ineff= 2 ,-1
       0  564.72   29.47 1613.66 2495.88   26.38
Permanent Ineff=
       F       F
Bank Sta=616.45,690.87
XS Rating Curve= 0
Exp/Cntr=0.3,0.1

Type RM Length L Ch R = 1 ,1273.079,412.74,419.56,450.83
XS GIS Cut Line= 6
     3193768.216    13831315.907     3193790.038    13831333.365
      3194049.48     13831331.05     3194313.998    13831348.983
     3196330.872    13831420.824     3196748.996    13831622.824
#Sta/Elev= 30
       0   29.78   42.53   28.41  237.54   27.69  297.57   29.45  366.48   26.73
  553.15   28.19  583.17   26.19   621.9   25.87  644.19   23.32  658.22   20.97
  673.23   15.99  688.24   14.74  722.58   23.48  733.27   25.12  763.29   25.62
  898.14   24.39 1603.82   25.13 1663.86   20.69  1694.4    23.3 1768.92    23.8
  1786.7      22 1828.96   24.39 1858.98   21.72  2204.2   21.84 2249.23   23.95
 2279.25   21.88 2597.06   22.09 2647.03   24.85 2796.96   23.35 3035.04   24.02
#Mann= 5 ,-1 , 0
       0     .99       0  553.15     .06       0  644.19     .04       0
  722.58     .06       0  763.29      .5       0
#XS Ineff= 2 ,-1
       0  555.15   28.21 1600.82 2643.45   24.91
Permanent Ineff=
       F       F
Bank Sta=644.19,722.58
XS Rating Curve= 0
Exp/Cntr=0.3,0.1

Type RM Length L Ch R = 1 ,853.522 ,355.14,385.14,418.89
XS GIS Cut Line= 6
     3193738.777    13831718.387      3194091.43    13831749.541
     3194367.798    13831761.453     3194494.208    13831785.999
     3195381.258    13831933.403      3195915.81     13832163.35
#Sta/Elev= 30
       0   26.27   51.05   23.02  174.37   22.55  291.98   23.74  352.22   27.18
  397.26   25.06  496.82   23.07  562.42   24.08  622.47   27.01  655.02   23.41
  683.45   15.22  698.73    15.2  741.76   23.64  775.05   24.81  790.26   23.73
  837.08   25.28 1596.16   24.66 1641.78   25.14 1656.98   26.92 1673.19   27.15
 1712.01   25.92 1722.18   26.41  1738.5   29.97 1754.83   29.26 1787.49   20.77
 1803.54    19.5 2043.12   19.71 2065.08   21.28 2123.04   30.77 2240.55   31.54
#Mann= 6 ,-1 , 0
       0     .99       0  622.47     .06       0  655.02     .04       0
  741.76     .06       0  775.05      .2       0 1673.19     .99       0
#XS Ineff= 2 ,-1
       0   618.7   27.28 1739.23 2115.03   29.94
Permanent Ineff=
       F       F
Bank Sta=655.02,741.76
XS Rating Curve= 0
Exp/Cntr=0.3,0.1

Type RM Length L Ch R = 1 ,468.385 ,571.01,376.84,229.08
XS GIS Cut Line= 6
     3193661.133    13832070.774     3194296.291    13832108.916
     3194322.333    13832098.499     3194457.466    13832196.339
     3194686.117    13832245.656     3195667.945    13832482.887
#Sta/Elev= 30
       0   24.53   38.56   22.55  118.76    22.4  173.78   22.78  215.79   25.37
  278.96   23.35  414.18   27.19  499.41   25.14  644.52   26.08  706.27   23.58
  731.63   16.28  747.43   15.52  753.12   15.65   785.7   23.47  807.08   23.67
  913.81   23.95 1150.69   24.53 1269.34   26.43 1390.69   23.47 1577.96   23.55
 1625.25   25.85 1670.55   25.25  1701.4   29.82 1713.86   28.31 1738.71   20.85
 1751.14   19.22 1988.81   19.41 2025.47   21.32 2056.33   30.19 2075.18   31.92
#Mann= 6 ,-1 , 0
       0     .99       0  644.52     .06       0  706.27     .04       0
  807.08     .06       0  913.81      .5       0  1701.4     .99       0
#XS Ineff= 2 ,-1
       0  639.32   26.41 1700.28 2053.16   29.76
Permanent Ineff=
       F       F
Bank Sta=706.27,807.08
XS Rating Curve= 0
Exp/Cntr=0.3,0.1

Type RM Length L Ch R = 1 ,91.541  ,137.47,78.79,484.97
XS GIS Cut Line= 6
     3193819.408     13832635.19     3194016.506    13832420.174
     3194440.564    13832473.928     3194721.279    13832429.133
     3195234.928    13832617.272        3195656.    13832835.273
#Sta/Elev= 30
       0   18.82   204.7   17.87  322.37   14.33  347.97   14.93  431.47   14.75
  563.46   17.44  750.89   22.84  803.25   18.98   856.4    19.8  895.98   18.76
  931.97   20.07  968.04      17  986.67   18.23 1104.88   16.92 1205.46   18.81
 1232.56   15.47 1365.97   21.66 1456.25   23.45 1504.24   22.84 1552.24   29.63
 1611.99    28.3 1620.37   26.91 1641.77   26.28 1686.01   28.45 1759.46   27.39
 1784.71   30.01 1812.82   27.98 1844.24   29.54 1891.38   27.16 2039.46   27.06
#Mann= 3 , 0 , 0
       0     .06       0  347.97     .06       0  563.46     .06       0
Bank Sta=347.97,563.46
XS Rating Curve= 0
Exp/Cntr=0.3,0.1

Type RM Length L Ch R = 1 ,12.748  ,,,
XS GIS Cut Line= 6
     3193944.834    13832799.438     3193992.615    13832605.326
     3194049.356    13832527.682     3194234.508    13832506.777
     3194494.318    13832700.889     3195034.844    13833038.344
#Sta/Elev= 30
       0    5.25     7.5    4.11   30.16    3.04   57.08    3.59    88.1    2.62
  151.95    3.36  199.91    4.99  237.21    2.79  296.07    5.08   316.6     3.5
  358.26    1.51  413.68    2.49   464.8    2.17  482.12    2.87  499.43    2.02
  524.83    2.12  612.91    2.25   678.5     3.6  739.71    2.28  810.15     2.5
  817.36    3.01  843.54     1.9   876.6       2  885.16    2.75  903.66    1.92
  926.18    2.64 1007.09    1.74 1301.89    2.13 1408.13     2.9 1449.97    2.48
#Mann= 3 , 0 , 0
       0     .06       0   316.6     .06       0  524.83     .06       0
#XS Ineff= 2 , 0
          294.62    5.07
Permanent Ineff=
       F       F
Bank Sta=316.6,524.83
XS Rating Curve= 0
Exp/Cntr=0.3,0.1

River Reach=G105_ovl        ,DS_L
Reach XY= 30
     3193592.238    13826478.234     3193469.074      13826833.1
     3193440.729    13827072.152     3193429.618    13827429.715
     3193488.202    13827454.966     3193545.775    13827574.154
     3193480.121    13827649.909     3193225.585    13827582.234
     3191330.703     13827522.64     3191329.693    13827682.231
     3191174.143    13827848.891     3191104.449    13828179.183
     3190735.775    13828177.162     3190704.463    13828804.413
     3190745.876    13828898.349     3190703.453    13828931.681
     3190672.141    13829289.244     3191099.399    13829329.646
     3191107.479    13829425.602     3190911.527    13829730.642
     3190410.535    13829989.218     3190074.183    13829978.108
     3190015.599    13830078.104     3189871.462    13832680.978
     3189844.898     13832980.02     3189765.103    13833192.133
     3189755.003    13833750.699     3189811.566    13834169.876
     3189771.164    13834251.691     3189743.329    13834674.494

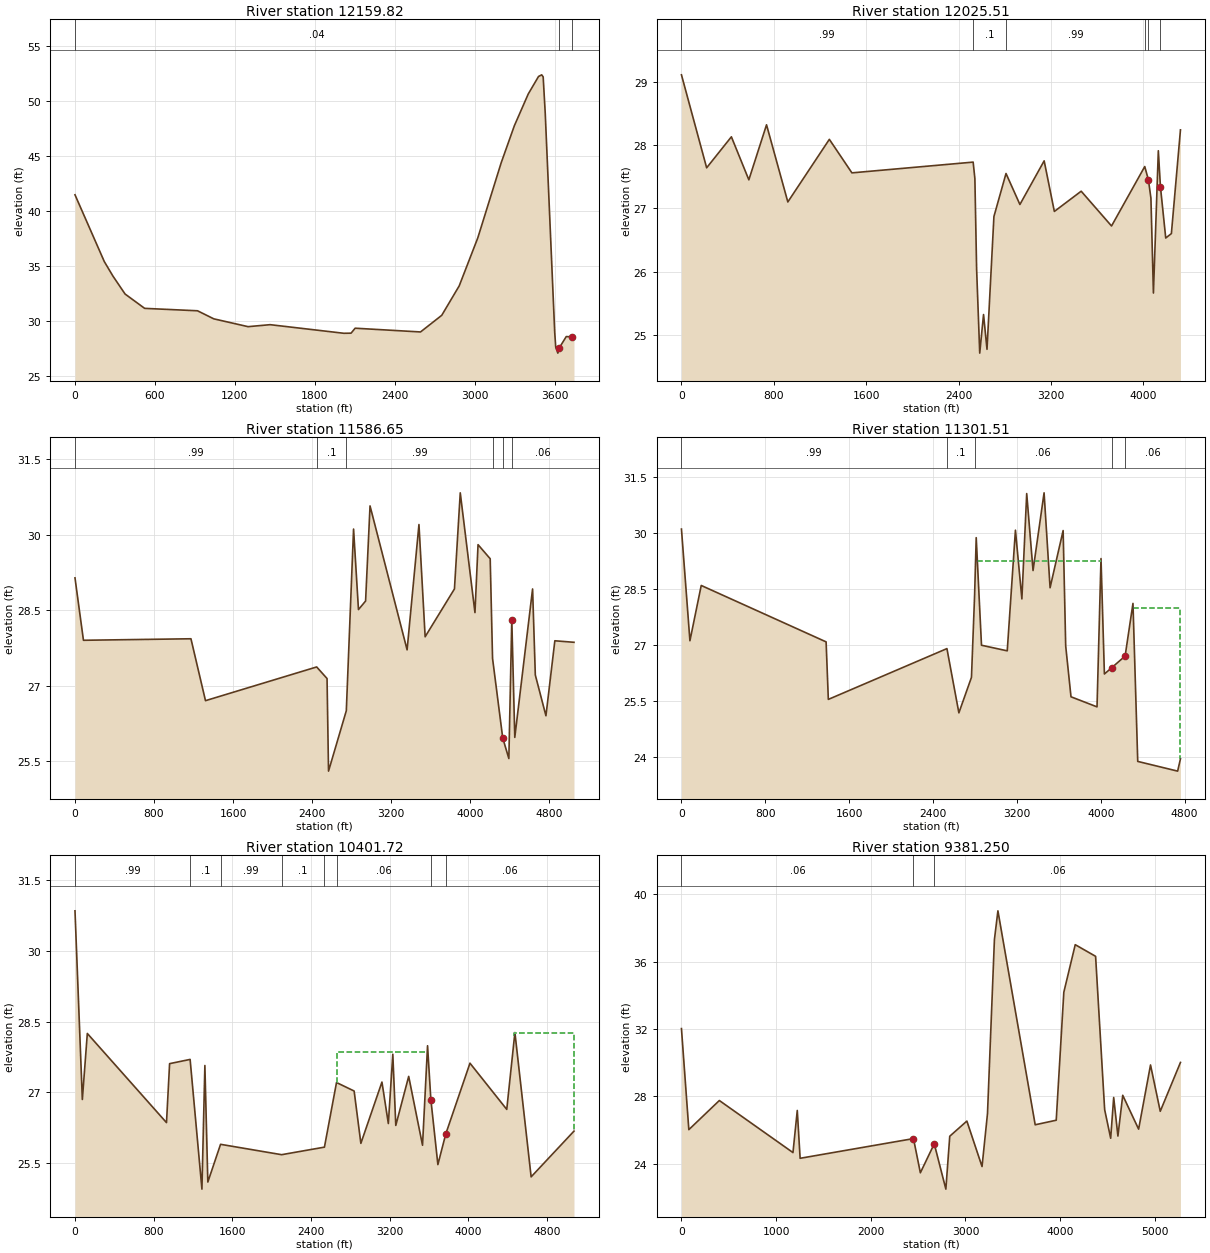
Type RM Length L Ch R = 1 ,12159.82,1443.21,134.31,126.98
XS GIS Cut Line= 6
     3189873.674    13826532.125      3190809.59    13826534.223
      3191330.01    13826492.254     3192393.932    13826471.269
     3193387.984    13826511.879     3193604.951    13826581.855
#Sta/Elev= 30
       0   41.47  220.13   35.41  284.65    34.1  375.95   32.47  522.81   31.17
  919.61   30.95 1041.58   30.22 1298.76   29.51 1464.66   29.69 2017.67   28.91
 2071.95   28.92  2102.7   29.37  2593.2   29.03 2752.57   30.54 2883.63   33.21
 3022.97   37.56 3198.46   44.37 3297.42   47.73 3401.62   50.61 3478.85    52.2
 3502.58   52.35 3513.72   52.16 3529.31   48.84 3600.44   28.97 3608.12   27.64
 3623.88   27.11 3636.19   27.62 3686.92   28.61 3729.66   28.59 3745.05   28.56
#Mann= 3 , 0 , 0
       0     .04       0 3636.19    .015       0 3729.66     .02       0
Bank Sta=3636.19,3729.66
XS Rating Curve= 0
Exp/Cntr=0.3,0.1

Type RM Length L Ch R = 1 ,12025.51,144.6,438.87,427.9
XS GIS Cut Line= 4
     3189418.349    13826636.823     3193429.381    13826676.203
     3193675.507    13826722.967     3193716.944    13826679.228
#Sta/Elev= 30
       0   29.11  218.19   27.64  432.43   28.13   583.7   27.45  736.86   28.32
  921.32    27.1 1280.96   28.09 1476.35   27.56  2526.4   27.73  2541.4   27.47
  2556.4   26.04 2583.43   24.71  2616.4   25.32 2646.41   24.77 2706.41   26.87
 2811.05   27.55 2931.42   27.06 3141.43   27.75 3229.75   26.95  3462.1   27.27
 3724.98   26.72 4012.72   27.66 4044.36   27.45 4066.14   27.16 4087.82   25.66
 4130.29   27.91 4148.56   27.34 4194.44   26.53 4243.36    26.6 4322.01   28.24
#Mann= 6 ,-1 , 0
       0     .99       0  2526.4      .1       0 2811.05     .99       0
 4012.72     .06       0 4044.36     .02       0 4148.56     .06       0
Bank Sta=4044.36,4148.56
XS Rating Curve= 0
Exp/Cntr=0.3,0.1

Type RM Length L Ch R = 1 ,11586.65,188.5,285.14,301.57
XS GIS Cut Line= 6
     3189409.185    13826732.649     3193293.191    13826815.674
     3193293.483    13827017.601     3193263.843    13827041.852
      3193255.76    13827118.646     3194103.262    13827152.486
#Sta/Elev= 30
       0   29.14   85.67    27.9 1173.69   27.93 1320.84    26.7 2446.18   27.37
 2551.21   27.14 2566.21    25.3 2746.27    26.5 2819.57   30.11 2869.25   28.51
 2941.33   28.68 2986.34   30.57 3361.47   27.71 3481.49    30.2 3544.09   27.97
 3840.71   28.92 3899.55   30.83 4048.35   28.45 4079.55    29.8 4202.51   29.52
 4226.38   27.54  4329.3   25.96 4391.43   25.55 4421.13   28.31 4451.44   25.97
 4631.57   28.92 4659.23   27.21 4766.75    26.4 4856.87   27.89 5050.75   27.86
#Mann= 6 ,-1 , 0
       0     .99       0 2446.18      .1       0 2746.27     .99       0
 4226.38     .06       0  4329.3     .03       0 4421.13     .06       0
Bank Sta=4329.3,4421.13
XS Rating Curve= 0
Exp/Cntr=0.3,0.1

Type RM Length L Ch R = 1 ,11301.51,751.95,899.79,862.66
XS GIS Cut Line= 6
     3189388.814     13826905.92     3192196.309    13826978.273
     3192543.328    13827124.152     3192991.277    13827157.789
     3193287.606    13827388.127     3194028.305    13827491.824
#Sta/Elev= 30
       0    30.1   80.84   27.11  188.69   28.59 1379.95   27.08 1401.28   25.54
 2532.67    26.9 2646.69   25.18 2766.73   26.13 2796.74   28.33 2812.03   29.87
 2862.41   26.99 3108.04   26.84 3186.19   30.07 3247.66   28.23 3293.75   31.05
 3354.17   28.99 3459.46   31.07 3516.83   28.53 3641.25   30.06 3665.69   26.97
 3716.29   25.61 3964.61   25.34  4002.6   29.31 4034.95   26.22 4105.48   26.39
 4232.58    26.7 4307.58   28.11 4353.02   23.88 4733.75   23.62 4760.63   23.95
#Mann= 5 ,-1 , 0
       0     .99       0 2532.67      .1       0 2796.74     .06       0
 4105.48     .03       0 4232.58     .06       0
#XS Ineff= 3 ,-1
                         2816.77 4001.82   29.25  4307.2 4767.55      28
Permanent Ineff=
       F       F       F
Bank Sta=4105.48,4232.58
XS Rating Curve= 0
Exp/Cntr=0.3,0.1

Type RM Length L Ch R = 1 ,10401.72,361.67,1020.47,803.54
XS GIS Cut Line= 6
     3189424.913    13827153.687     3192798.745    13827348.623
     3192917.256     13827477.01     3192927.132    13827881.926
      3193278.89    13828251.911     3193880.165    13828272.027
#Sta/Elev= 30
       0   30.85   74.77   26.85  125.38   28.25  930.38   26.36  961.92   27.61
 1170.55    27.7 1290.64   24.95 1320.66   27.57 1350.68    25.1 1480.07    25.9
 2100.77   25.68 2536.22   25.84 2659.09   27.21 2838.25   27.03 2906.72   25.92
 3121.01   27.22 3186.09   26.34 3231.46   27.81 3261.71    26.3 3392.94   27.34
 3533.59   25.88 3584.68   27.99  3618.3   26.85 3689.71   25.47 3769.95   26.12
 4015.98   27.62 4390.01   26.64 4472.81   28.27  4637.9   25.21 5073.69   26.18
#Mann= 8 ,-1 , 0
       0     .99       0 1170.55      .1       0 1480.07     .99       0
 2100.77      .1       0 2536.22     .99       0 2659.09     .06       0
  3618.3     .04       0 3769.95     .06       0
#XS Ineff= 3 ,-1
                         2659.09  3582.5   27.85 4468.55 5092.07   28.27
Permanent Ineff=
       F       F       F
Bank Sta=3618.3,3769.95
XS Rating Curve= 0
Exp/Cntr=0.3,0.1

Type RM Length L Ch R = 1 ,9381.250,704.85,1163.44,831.12
XS GIS Cut Line= 6
     3189566.347    13827547.542     3189880.011    13827375.147
      3191904.08     13827398.48     3191896.798    13827759.659
     3193519.692    13829254.688     3193835.723    13829264.564
#Sta/Elev= 30
       0   32.02   77.91   26.02  400.22   27.75 1177.92   24.66 1223.37   27.16
  1253.4   24.32 2450.85   25.49 2523.54   23.46 2670.23   25.18 2792.81   22.49
 2833.99   25.63 3014.79   26.53 3174.96   23.83  3232.7   26.98 3305.71    37.3
 3342.67   39.01 3736.42   26.31 3958.58   26.58 4038.91   34.18 4159.43      37
 4374.48   36.31 4470.05   27.21 4533.76   25.51 4565.62   27.93 4610.21   25.64
 4661.19   28.06 4828.93   26.05 4954.61   29.86 5057.42   27.11 5270.88   30.01
#Mann= 3 , 0 , 0
       0     .06       0 2450.85     .04       0 2670.23     .06       0
Bank Sta=2450.85,2670.23
XS Rating Curve= 0
Exp/Cntr=0.3,0.1