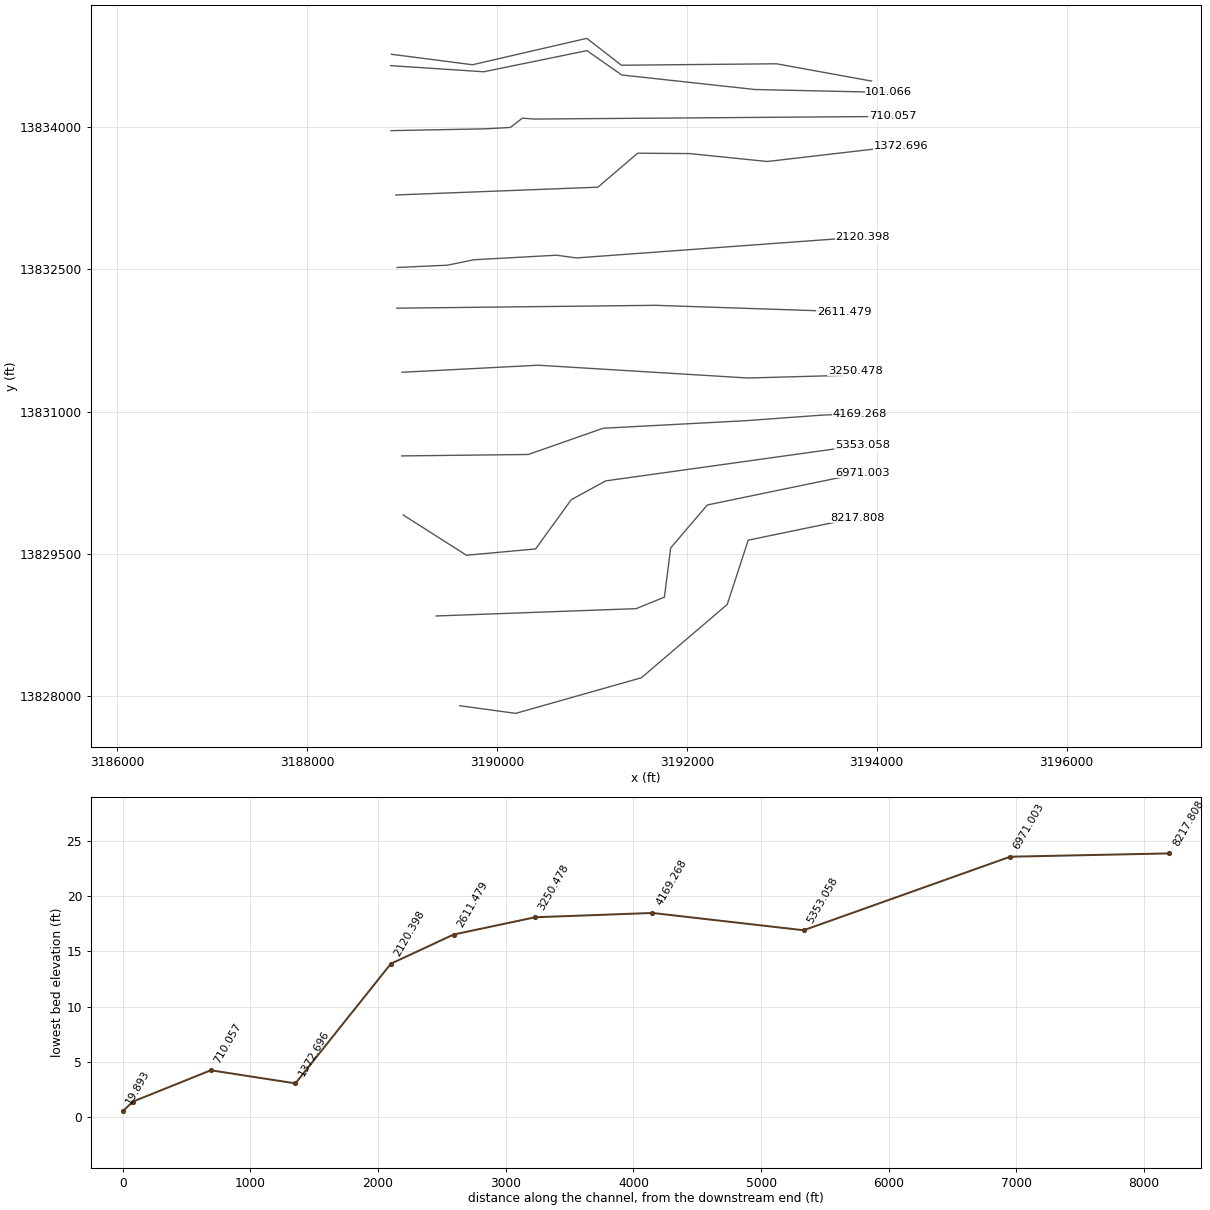
HEC-RAS study G105_ovrlnd.prj: G105 overland flow

--- G105_ovrlnd.g04 (geometry) --- (continued)

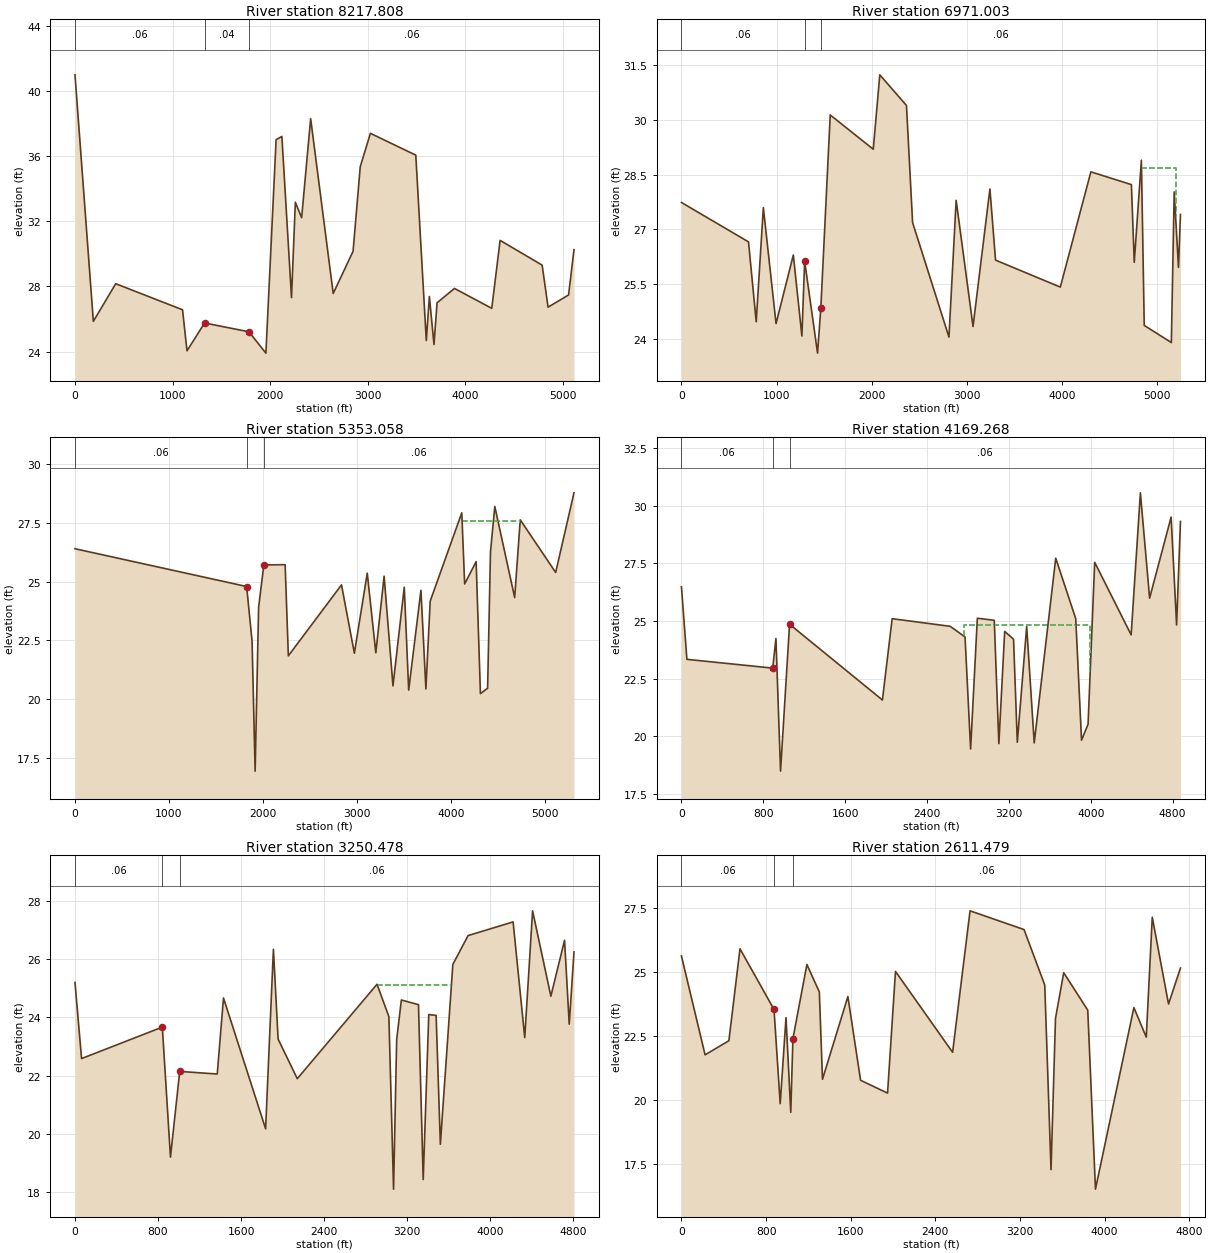
Type RM Length L Ch R = 1 ,8217.808,1000.89,1246.81,766.25
XS GIS Cut Line= 6
     3189609.445    13827901.911     3190197.639     13827821.26
      3191521.52    13828196.359     3192426.173    13828968.624
     3192646.827    13829645.654      3193800.27    13829884.498
#Sta/Elev= 30
       0   40.99  188.12   25.86   417.4   28.17 1102.39   26.57 1147.99   24.05
 1328.18   25.76 1782.71   25.22 1956.79   23.91 2061.33   37.01 2120.49   37.21
  2219.1   27.32 2258.55   33.17 2323.05   32.22 2415.46    38.3 2646.49   27.57
 2850.21   30.16 2923.73   35.35 3027.71    37.4 3493.02   36.06 3600.64   24.68
 3632.19   27.39 3679.52   24.44 3711.08      27 3889.44   27.88 4271.54   26.66
 4357.31   30.83 4788.05   29.31 4848.75   26.73 5058.83   27.48 5114.49   30.26
#Mann= 3 , 0 , 0
       0     .06       0 1328.18     .04       0 1782.71     .06       0
Bank Sta=1328.18,1782.71
XS Rating Curve= 0
Exp/Cntr=0.3,0.1

Type RM Length L Ch R = 1 ,6971.003,725.5,1617.94,1207.88
XS GIS Cut Line= 6
      3189359.18    13828847.268     3191466.359    13828924.494
     3191764.232     13829045.85     3191830.426     13829564.37
     3192216.558    13830016.697     3193855.475    13830355.861
#Sta/Elev= 30
       0   27.74  705.05   26.66  785.97   24.47  861.02    27.6  994.65   24.42
 1176.24    26.3  1266.3   24.08 1295.47   26.13 1430.92   23.61  1465.3   24.84
 1564.29   30.14  2016.8    29.2 2085.33   31.24 2365.88    30.4 2430.24   27.19
 2812.62   24.05 2888.23    27.8 3065.76   24.34 3243.26   28.11 3302.43   26.16
 3983.44   25.42 4304.84   28.58 4730.87   28.23 4760.87    26.1 4835.87    28.9
 4865.87   24.37 5150.87    23.9 5180.87   28.03 5225.87   25.96 5246.72   27.41
#Mann= 3 , 0 , 0
       0     .06       0 1295.47     .04       0  1465.3     .06       0
#XS Ineff= 1 ,-1
    4835 5195.99   28.69
Permanent Ineff=
       F
Bank Sta=1295.47,1465.3
XS Rating Curve= 0
Exp/Cntr=0.3,0.1

Type RM Length L Ch R = 1 ,5353.058,1337.35,1183.79,605.92
XS GIS Cut Line= 6
     3189013.244    13829910.798     3189679.118    13829487.144
     3190407.253    13829553.338     3190782.353    13830071.858
      3191146.42    13830270.441     3193851.243    13830647.635
#Sta/Elev= 30
       0    26.4 1827.25   24.79 1885.02   22.46 1917.55   16.93 1954.58    23.9
 2010.24   25.71 2236.96   25.72 2271.13   21.84 2836.98   24.86 2973.94   21.95
 3110.89   25.36  3202.2   21.97 3290.57   25.23  3384.8   20.56 3504.96   24.76
 3552.19   20.38 3682.54   24.63 3735.37   20.43  3781.2   24.17 4117.28   27.93
 4147.84    24.9 4270.05   25.85 4315.88   20.23 4392.26   20.46 4422.82   26.26
 4468.65    28.2 4680.24   24.32 4739.77   27.63 5116.67   25.39 5311.76   28.78
#Mann= 3 , 0 , 0
       0     .06       0 1827.25     .04       0 2010.24     .06       0
#XS Ineff= 2 ,-1
 3292.62 3943.48   25.12  4118.5 4736.55   27.58
Permanent Ineff=
       F       F
Bank Sta=1827.25,2010.24
XS Rating Curve= 0
Exp/Cntr=0.3,0.1

Type RM Length L Ch R = 1 ,4169.268,913.75,918.79,911.25
XS GIS Cut Line= 6
     3188996.483    13830533.338     3190329.748    13830548.442
     3191119.827     13830824.97     3192616.039    13830903.978
      3193425.87    13830963.234     3193820.909    13830978.048
#Sta/Elev= 30
       0   26.48   53.15   23.34  891.68   22.96   923.2   24.24  968.21    18.5
 1056.34   24.86 1963.61   21.58 2058.97    25.1 2626.24   24.77 2771.06   24.31
 2825.49   19.46 2891.23   25.12 3056.46   25.03 3101.52   19.69 3158.52   24.55
 3244.96   24.21 3281.77   19.75  3373.4   24.76    3447   19.72 3657.29   27.72
  3852.8    25.1 3909.33   19.84 3973.12   20.53 4037.91   27.54 4394.24    24.4
 4484.47   30.55 4574.54   25.99 4784.68    29.5 4838.25   24.83 4876.03   29.31
#Mann= 3 , 0 , 0
       0     .06       0  891.68     .04       0 1056.34     .06       0
#XS Ineff= 1 ,-1
 2762.08 3992.71   24.84
Permanent Ineff=
       F
Bank Sta=891.68,1056.34
XS Rating Curve= 0
Exp/Cntr=0.3,0.1

Type RM Length L Ch R = 1 ,3250.478,651.58,639,621
XS GIS Cut Line= 6
     3189001.272    13831414.471     3190435.508    13831488.697
     3192645.371    13831353.972     3193642.982    13831381.643
     3193679.391    13831428.247     3193775.512     13831431.16
#Sta/Elev= 30
       0    25.2   63.44   22.59  841.23   23.67  919.58   19.21 1008.73   22.15
 1370.18   22.06 1430.27   24.67 1836.01   20.18 1911.15   26.34 1956.24   23.26
 2140.93    21.9 2909.09   25.14 3023.21   24.03  3068.3   18.11 3098.35   23.24
 3143.44    24.6 3308.36   24.44 3353.83   18.44 3407.51    24.1 3478.33   24.07
 3519.13   19.65 3639.36   25.82 3785.87   26.81 4219.67   27.28  4331.8   23.31
 4407.37   27.66 4583.44   24.73 4715.27   26.65 4760.29   23.77  4806.2   26.25
#Mann= 3 , 0 , 0
       0     .06       0  841.23     .04       0 1008.73     .06       0
#XS Ineff= 1 ,-1
 2907.93 3623.52    25.1
Permanent Ineff=
       F
Bank Sta=841.23,1008.73
XS Rating Curve= 0
Exp/Cntr=0.3,0.1

Type RM Length L Ch R = 1 ,2611.479,465.89,491.08,525.21
XS GIS Cut Line= 5
     3188946.201    13832089.687     3191670.233    13832119.709
     3193399.769    13832061.767      3193603.66    13832077.787
     3193656.089    13832051.572
#Sta/Elev= 30
       0   25.62  223.44   21.77  448.45   22.32  553.46    25.9  874.97   23.54
  933.57   19.87  988.48   23.22 1033.49   19.53 1053.78    22.4 1186.03   25.29
  1303.5   24.22 1333.51   20.82 1573.52   24.04 1693.53   20.78 1948.54   20.28
 2023.55   25.02 2563.58   21.87 2728.59   27.38 3238.88   26.65 3434.75   24.49
 3494.02    17.3  3536.4   23.19 3614.09   24.97 3841.36   23.51 3914.26   16.54
 4277.58   23.61 4394.53   22.46 4451.28   27.13 4605.02   23.75 4717.84   25.15
#Mann= 3 , 0 , 0
       0     .06       0  874.97     .04       0 1053.78     .06       0
Bank Sta=874.97,1053.78
XS Rating Curve= 0
Exp/Cntr=0.3,0.1

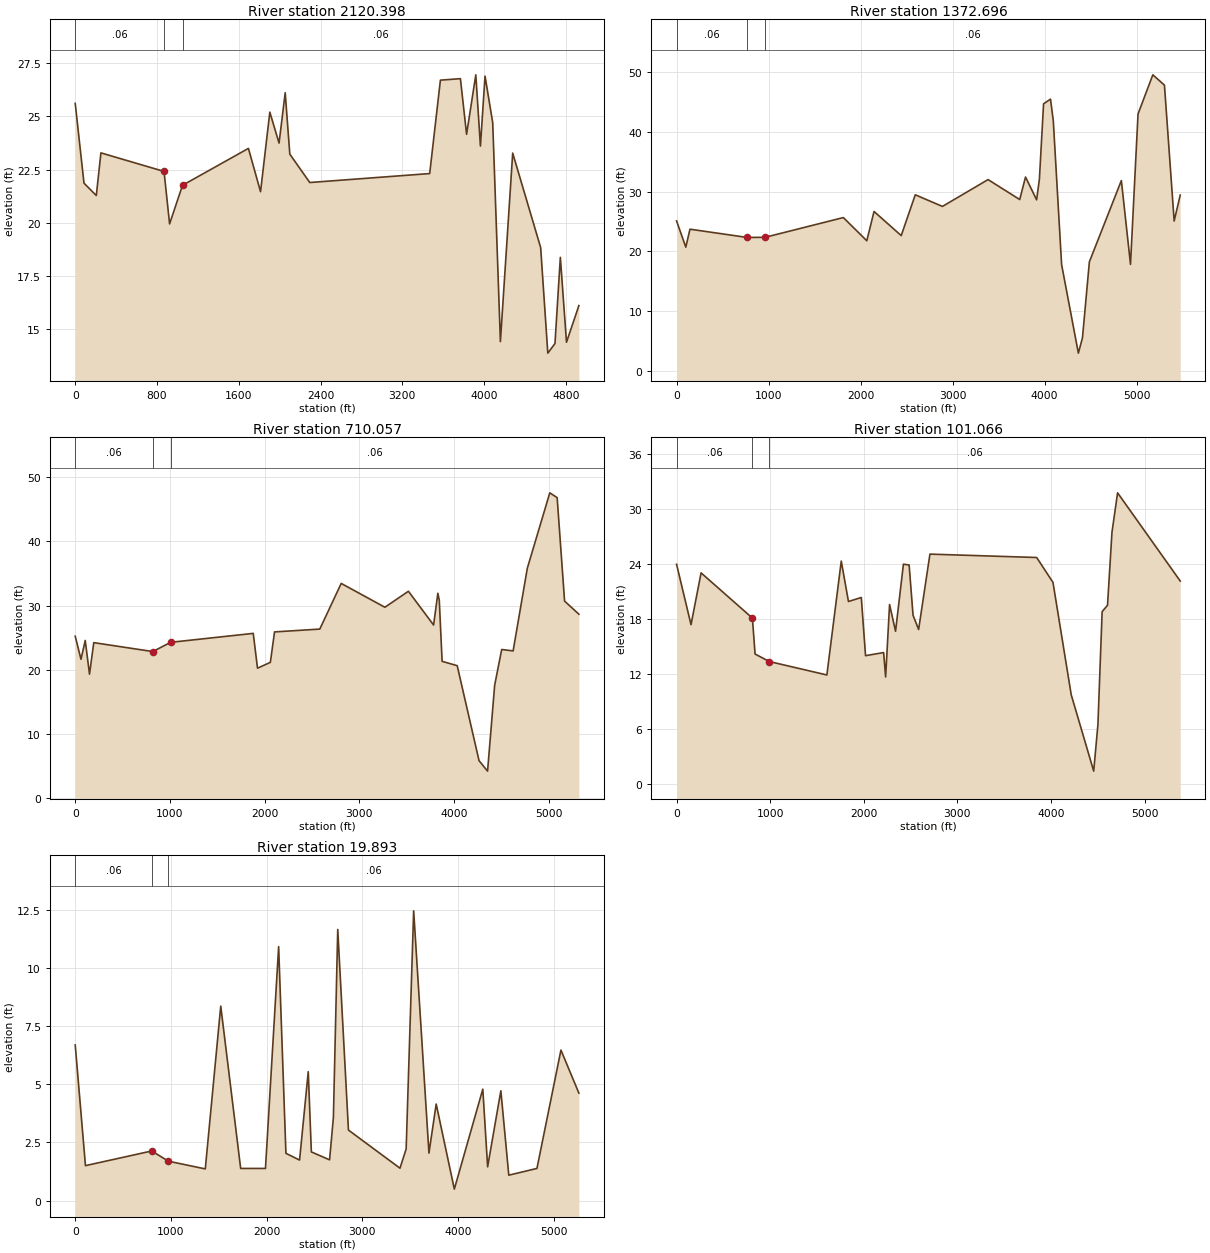
Type RM Length L Ch R = 1 ,2120.398,749.22,747.7,722.43
XS GIS Cut Line= 6
     3188948.596    13832518.282     3189477.754    13832542.225
     3189757.897    13832599.691     3190627.058    13832647.578
     3190837.764    13832618.846     3193850.537    13832839.671
#Sta/Elev= 30
       0    25.6   85.76   21.86  206.29   21.28  251.43   23.28  868.98   22.41
  923.38   19.95 1049.85   21.76 1694.65   23.49 1813.31   21.46 1904.14   25.19
  1994.4   23.74 2054.56    26.1 2099.68   23.22 2295.21   21.89 3468.34   22.31
 3573.16   26.69 3768.92   26.76 3829.31   24.15 3919.55   26.94 3964.67    23.6
 4009.79   26.88 4084.99    24.7  4160.2   14.43 4280.52   23.27 4554.08   18.84
 4624.14   13.89 4694.21   14.34 4746.76   18.38 4806.92    14.4 4928.16   16.12
#Mann= 3 , 0 , 0
       0     .06       0  868.98     .04       0 1049.85     .06       0
Bank Sta=868.98,1049.85
XS Rating Curve= 0
Exp/Cntr=0.3,0.1

Type RM Length L Ch R = 1 ,1372.696,669.98,662.64,666.7
XS GIS Cut Line= 6
     3188934.229     13833282.09      3191063.24    13833364.045
     3191482.246     13833721.99      3192029.37    13833718.124
     3192848.124    13833634.688     3194260.069    13833799.056
#Sta/Elev= 30
       0   25.09  100.51   20.71  145.57   23.71  767.82   22.33  961.04   22.35
  1812.5   25.65 2067.53   21.78 2146.13   26.67 2441.46   22.64  2594.2   29.45
 2889.62   27.51 3385.43   31.99 3729.47   28.66 3792.53   32.42 3913.15   28.61
  3943.3   32.06 3988.54   44.64 4063.94   45.42 4094.15   41.85 4184.75   17.79
 4366.88    3.02 4411.27    5.57 4486.51   18.26 4834.11   31.83 4933.37   17.84
 5015.32   42.95 5176.14   49.48 5302.25   47.76 5407.96   25.08 5473.84    29.4
#Mann= 3 , 0 , 0
       0     .06       0  767.82     .04       0  961.04     .06       0
Bank Sta=767.82,961.04
XS Rating Curve= 0
Exp/Cntr=0.3,0.1

Type RM Length L Ch R = 1 ,710.057 ,623.66,608.99,612.13
XS GIS Cut Line= 6
     3188883.947      13833959.7     3189877.616    13833978.855
     3190140.998    13833993.222     3190267.901    13834091.391
     3190392.409    13834081.814     3194169.284    13834109.698
#Sta/Elev= 30
       0   25.22   60.75   21.63  105.81   24.56  150.87   19.31  195.92   24.22
  819.42   22.83 1008.29   24.27 1880.48   25.66 1925.48   20.24 2061.13   21.15
 2105.48   25.89 2583.45   26.33 2809.63   33.44 3271.23   29.73 3519.53   32.22
 3785.52   26.96 3830.52   31.91 3845.52    30.8 3875.52   21.31 4034.86   20.63
 4265.53    5.84 4355.53    4.21 4430.53   17.58 4504.86   23.15 4625.54   22.93
 4775.54   35.81 5012.97   47.55 5090.55    46.8 5169.13   30.69 5320.21   28.65
#Mann= 3 , 0 , 0
       0     .06       0  819.42     .04       0 1008.29     .06       0
Bank Sta=819.42,1008.29
XS Rating Curve= 0
Exp/Cntr=0.3,0.1

Type RM Length L Ch R = 1 ,101.066 ,87.61,81.17,127.36
XS GIS Cut Line= 6
     3188881.553    13834644.494     3189860.856    13834579.845
     3190947.906    13834802.523     3191314.246    13834546.324
     3192717.355    13834393.084     3194127.646    13834361.957
#Sta/Elev= 30
       0   23.98  154.49   17.38     262   23.04  810.16    18.1  838.61   14.17
  990.72   13.35 1605.67   11.88 1759.36   24.33 1836.21   19.91 1973.37   20.35
 2018.72   13.99 2211.92   14.33 2233.36   11.66 2275.37   19.58 2339.32   16.66
 2423.34   23.99 2484.39    23.9 2526.13   18.41 2585.73   16.85 2706.64   25.09
 3846.91   24.72 4020.96      22 4215.98    9.71 4456.02    1.37 4501.02    6.45
 4546.03    18.8  4603.6    19.5 4651.03   27.47 4711.09   31.79 5380.27   22.15
#Mann= 3 , 0 , 0
       0     .06       0  810.16     .04       0  990.72     .06       0
Bank Sta=810.16,990.72
XS Rating Curve= 0
Exp/Cntr=0.3,0.1

Type RM Length L Ch R = 1 ,19.893  ,,,
XS GIS Cut Line= 6
     3188888.736    13834764.213     3189743.031    13834653.904
       3190946.9    13834932.109     3191311.096    13834648.846
     3192944.918    13834664.021     3193946.456    13834481.923
#Sta/Elev= 30
       0    6.69  107.02     1.5  799.61    2.13  974.99    1.69 1359.72    1.36
 1521.23    8.36 1729.54    1.38 1988.83    1.38 2126.49   10.92  2202.5    2.03
  2345.2    1.74 2435.96    5.54 2468.54    2.09 2658.88    1.75 2698.82    3.57
 2744.27   11.66 2856.22    3.03 3395.06    1.39 3459.48    2.22 3537.85   12.46
 3697.73    2.04  3773.4    4.15 3963.07     .49 4260.72    4.79 4311.15    1.45
 4449.38    4.72 4532.32    1.09  4826.7    1.38 5077.45    6.47 5265.12    4.62
#Mann= 3 , 0 , 0
       0     .06       0  799.61     .04       0  974.99     .06       0
Bank Sta=799.61,974.99
XS Rating Curve= 0
Exp/Cntr=0.3,0.1

Chan Stop Cuts=-1

--- G105_ovrlnd.g02 (geometry) ---

Geom Title=Split Flow @ SH225
Program Version=3.11

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
River Reach=G105_ovl        ,US

River Reach=G105_ovl_R      ,DS_R

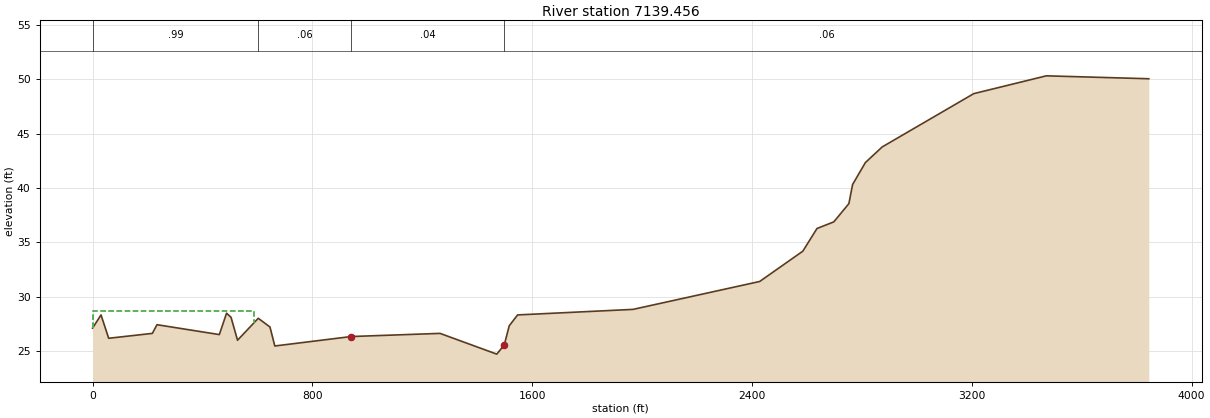
Type RM Length L Ch R = 1 ,7139.456,,,
XS GIS Cut Line= 6
     3194082.205    13827077.634     3194574.949    13827089.579
     3194874.416     13826772.11     3195221.638    13826735.652
       3195251.5    13826514.974     3197537.386    13826626.699
#Sta/Elev= 30
       0    27.1   30.65   28.31   58.54   26.16  217.48   26.61  234.33   27.41
  461.21    26.5  487.56   28.47  503.86   28.09  527.51   25.98  602.93      28
  645.52    27.2  663.19   25.45  941.44   26.32  1264.5   26.61 1470.97    24.7
 1498.17   25.54 1516.38   27.31 1546.84   28.31 1966.88   28.82 2427.88   31.39
 2584.82   34.18 2636.46   36.27 2697.65   36.88 2752.53   38.56 2766.03   40.32
 2812.51   42.34 2873.72   43.78 3207.03   48.69 3471.21   50.33 3844.04   50.06
#Mann= 4 ,-1 , 0
       0     .99       0  602.93     .06       0  941.44     .04       0
 1498.17     .06       0
#XS Ineff= 2 , 0
          586.62   28.64
Permanent Ineff=
       F       F
Bank Sta=941.44,1498.17
XS Rating Curve= 0
Exp/Cntr=0.3,0.1

River Reach=G105_ovl        ,DS_L

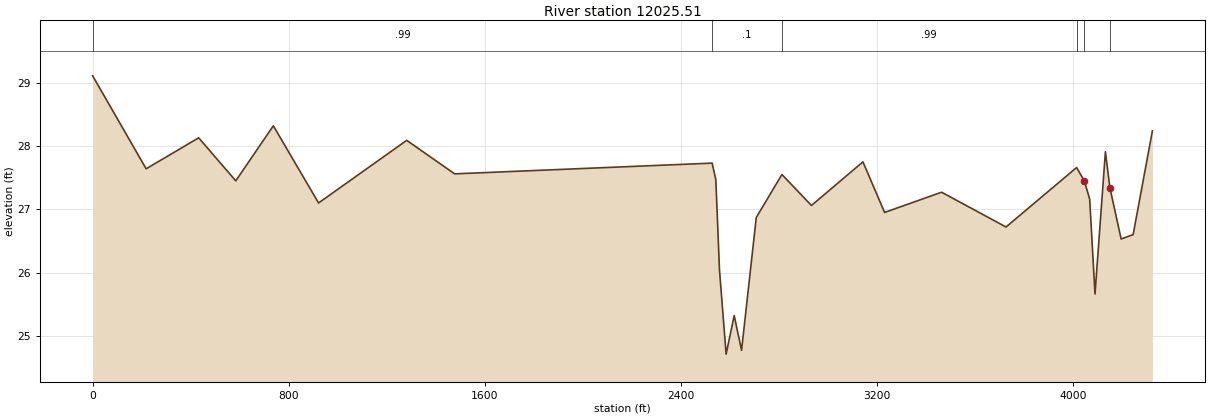
Type RM Length L Ch R = 1 ,12025.51,,,
XS GIS Cut Line= 4
     3189418.349    13826636.823     3193429.381    13826676.203
     3193675.507    13826722.967     3193716.944    13826679.228
#Sta/Elev= 30
       0   29.11  218.19   27.64  432.43   28.13   583.7   27.45  736.86   28.32
  921.32    27.1 1280.96   28.09 1476.35   27.56  2526.4   27.73  2541.4   27.47
  2556.4   26.04 2583.43   24.71  2616.4   25.32 2646.41   24.77 2706.41   26.87
 2811.05   27.55 2931.42   27.06 3141.43   27.75 3229.75   26.95  3462.1   27.27
 3724.98   26.72 4012.72   27.66 4044.36   27.45 4066.14   27.16 4087.82   25.66
 4130.29   27.91 4148.56   27.34 4194.44   26.53 4243.36    26.6 4322.01   28.24
#Mann= 6 ,-1 , 0
       0     .99       0  2526.4      .1       0 2811.05     .99       0
 4012.72     .06       0 4044.36     .02       0 4148.56     .06       0
Bank Sta=4044.36,4148.56
XS Rating Curve= 0
Exp/Cntr=0.3,0.1