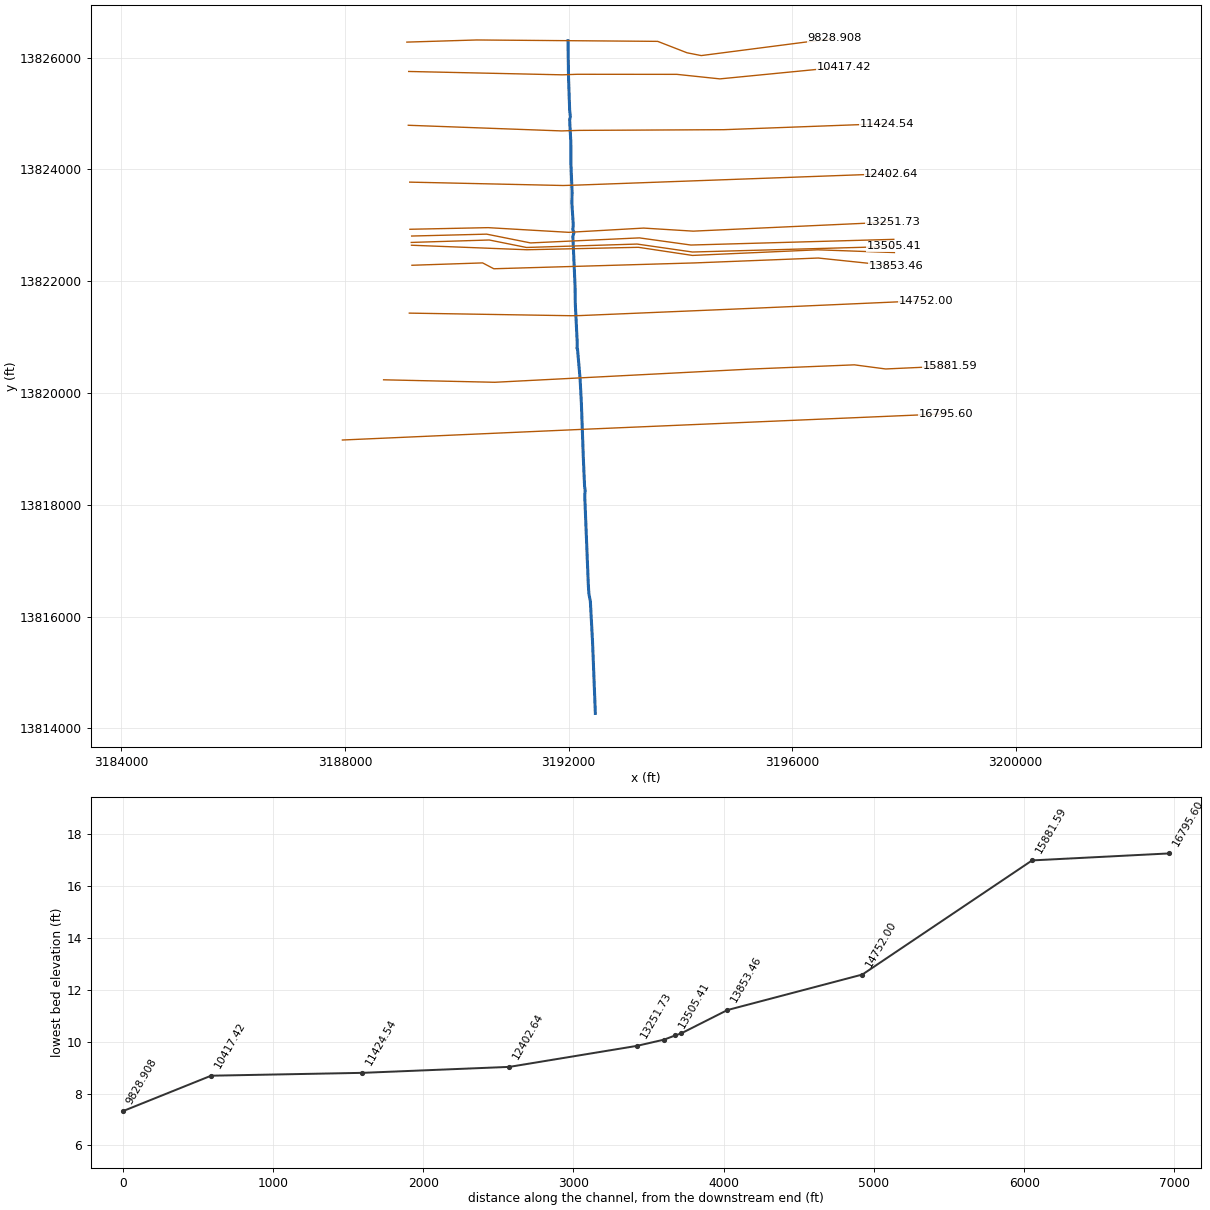
--- G105-00-00.prj (project) ---

Proj Title=G105-00-00
Current Plan=p01
Default Exp/Contr=.3,.1
English Units
Geom File=g06
Flow File=f04
Flow File=f01
Plan File=p01
Plan File=p03
Y Axis Title=Elevation
X Axis Title(PF)=Main Channel Distance
X Axis Title(XS)=Station
BEGIN DESCRIPTION:
& RHCFCD Unit G105-00-00 channel
Flood Hazard Model
10%, 2%, 1%, and 0.2% Events
File Name: G105_00_00.prj
Prepared by:  Nick Batker & Andrew Rooke - Turner Collie & Braden Inc.
January 2004
Reviewed by:  TC&B (Joe Barrow), Brown & Gay, Michael Baker Jr.
Status: Final Flows, Final Model
END DESCRIPTION:
DSS Export Rating Curves= 0
DSS Export Rating Curve Sorted= 0
DSS Export Volume Flow Curves= 0
DXF OffsetX= 0
DXF OffsetY= 0
DXF ScaleX= 1
DXF ScaleY= 10

--- G105-00-00.p01 (plan) ---

Plan Title=FEMA Effective June 2007
Version=Version 3.0.1  Mar 2001
Short Identifier=FEMAeff0607
Geom File=g06
Flow File=f04
Subcritical Flow
K Sum by GR= 0
Std Step Tol= 0.01
Critical Tol= 0.01
Num of Std Step Trials= 20
Max Error Tol= 0.3
Flow Tol Ratio= 0.001
Split Flow NTrial= 30
Split Flow Tol= 0.02
Split Flow Ratio= 0.02
Log Output Level= 0
Friction Slope Method= 0
Unsteady Friction Slope Method= 2
Secant Critical Depth
Global Vel Dist= 0 , 0 , 0
Global Log Level= 0
CheckData=True
Encroach Param=-1 ,0,0, 2
Computation Interval=1HOUR
Output Interval=1HOUR
Run HTab= 0
Run UNet= 0
Run PostProcess= 0
UNET Theta= 1
UNET ZTol= 0.02
UNET ZSATol= 0.1
UNET MxIter= 20
UNET MaxInSteps= 20
UNET DtIC= 0
UNET DtMin= 0
UNET MaxCRTS= 20
UNET WFStab= 2
UNET SFStab= 1
UNET WFX= 1
UNET SFX= 1
UNET Convert EG Bridges=-1
UNET Use Existing IB Tables=-1
Instantaneous Interval=1HOUR
Write IC File= 0
Write Velocity= 0
Write Detailed= 0

--- G105-00-00.p03 (plan) ---

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Plan Title=Floodway
Short Identifier=Floodway0607
Geom File=g06
Flow File=f01
Encroach River=G105-00-00
Encroach Reach=Channel
Encroach Node=16795.60
       1 4223.14 4370.42
Encroach Node=15881.59
       1 3468.71 3554.97
Encroach Node=14752.00
       1 2934.77 3051.47
Encroach Node=13853.46
       1  2871.8 2997.55
Encroach Node=13545.72
       1 2816.23 2967.67
Encroach Node=13505.41
       1 2826.22 2973.41
Encroach Node=13468.5
       1    2800    2970
Encroach Node=13431.67
       1 2801.79  2968.6
Encroach Node=13251.73
       1 2885.12 2999.01
Encroach Node=12402.64
       1 2840.46 2954.35
Encroach Node=11424.54
       1 2845.07 2951.31
Encroach Node=10417.42
       1 2808.47 2921.34
Encroach Node=9828.908
       1 2818.92  2938.9
Encroach Reach=G105-00-00_0098
Encroach Node=16795.60
       1 4223.14 4370.42
Encroach Node=15881.59
       1 3468.71 3554.97
Encroach Node=14752.00
       1 2934.77 3051.47
Encroach Node=13853.46
       1  2871.8 2997.55
Encroach Node=13545.72
       1 2816.23 2967.67
Encroach Node=13505.41
       1 2826.22 2973.41
Encroach Node=13468.5
       1    2800    2970
Encroach Node=13431.67
       1 2801.79  2968.6
Encroach Node=13251.73
       1 2885.12 2999.01
Encroach Node=12402.64
       1 2840.46 2954.35
Encroach Node=11424.54
       1 2845.07 2951.31
Encroach Node=10417.42
       1 2808.47 2921.34
Encroach Node=9828.908
       1 2818.92  2938.9

--- G105-00-00.f04 (steady flow) ---

Flow Title=FEMA Effective June 2007
Version=Version 3.0.1  Mar 2001
Number of Profiles= 4
Profile Names=10PCT_10yr, 2PCT_50yr, 1PCT_100yr, 0.2PCT_500yr
River Rch & RM=G105-00-00,G105-00-00_0098         ,16795.60
    1011    1358    1568    2183
River Rch & RM=G105-00-00,G105-00-00_0098         ,15881.59
    1077    1365    1574    2207
River Rch & RM=G105-00-00,G105-00-00_0098         ,14752.00
    1141    1372    1578    2229
River Rch & RM=G105-00-00,G105-00-00_0098         ,13853.46
    1164    1375    1580    2237
River Rch & RM=G105-00-00,G105-00-00_0098         ,13545.72
    1708    2140    2342    3247
River Rch & RM=G105-00-00,G105-00-00_0098         ,13251.73
    1678    2134    2358    3286
River Rch & RM=G105-00-00,G105-00-00_0098         ,12402.64
    1654    2129    2373    3320
River Rch & RM=G105-00-00,G105-00-00_0098         ,11424.54
    1628    2123    2388    3355
River Rch & RM=G105-00-00,G105-00-00_0098         ,10417.42
    1615    2121    2396    3375
Boundary for River Rch & Prof#=G105-00-00,G105-00-00_0098         , 1
Up Type= 0
Dn Type= 4
Dn Rating Curve # Pts= 33
       0    7.32     250    9.88     500   11.63     750   13.27    1000   14.85
    1200   17.42    1400   23.67    1500   26.14    1535      27    1539   27.11
    1545   27.24    1552   27.38    1564    27.6    1572   27.69    1593   27.84
    1615   27.93    1623   27.98    1682   28.19    1738   28.34    1792   28.46
    1895   28.66    1900   28.67    2112   28.97    2121   28.98    2143      29
    2371   29.22    2396   29.24    2628   29.41    3139   29.69    3375   29.78
    3647   29.89    3915   29.98    4153   30.06
Boundary for River Rch & Prof#=G105-00-00,G105-00-00_0098         , 2
Up Type= 0
Dn Type= 0
Boundary for River Rch & Prof#=G105-00-00,G105-00-00_0098         , 3
Up Type= 0
Dn Type= 0
Boundary for River Rch & Prof#=G105-00-00,G105-00-00_0098         , 4
Up Type= 0
Dn Type= 0
DSS Import GetInterval= 0
DSS Import GetPeak= 0
DSS Import FillOption= 0

--- G105-00-00.f01 (steady flow) ---

Flow Title=Floodway
Version=Version 3.0.1  Mar 2001
Number of Profiles= 2
Profile Names=1PCT_100yr, 1PCTFloodway_100yrFW
River Rch & RM=G105-00-00,G105-00-00_0098         ,16795.60
    1568    1568
River Rch & RM=G105-00-00,G105-00-00_0098         ,15881.59
    1574    1574
River Rch & RM=G105-00-00,G105-00-00_0098         ,14752.00
    1578    1578
River Rch & RM=G105-00-00,G105-00-00_0098         ,13853.46
    1580    1580
River Rch & RM=G105-00-00,G105-00-00_0098         ,13545.72
    2342    2342
River Rch & RM=G105-00-00,G105-00-00_0098         ,13251.73
    2358    2358
River Rch & RM=G105-00-00,G105-00-00_0098         ,12402.64
    2373    2373
River Rch & RM=G105-00-00,G105-00-00_0098         ,11424.54
    2388    2388
River Rch & RM=G105-00-00,G105-00-00_0098         ,10417.42
    2396    2396
Boundary for River Rch & Prof#=G105-00-00,G105-00-00_0098         , 1
Up Type= 0
Dn Type= 1
Dn Known WS=29.24
Boundary for River Rch & Prof#=G105-00-00,G105-00-00_0098         , 2
Up Type= 0
Dn Type= 1
Dn Known WS=30.14
Set Internal Change=G105-00-00      ,G105-00-00_0098         ,9828.908, 2 , 3 ,30.24
DSS Import GetInterval= 0
DSS Import GetPeak= 0
DSS Import FillOption= 0

--- G105-00-00.g06 (geometry) ---

Geom Title=G105-00-00 June 2007
Version=Version 3.0.1  Mar 2001

River Reach=G105-00-00      ,G105-00-00_0098
Reach XY= 30
     3192480.239    13814270.203     3192429.892    13815550.585
      3192390.83    13816273.676     3192364.749     13816409.09
     3192354.371    13816569.682     3192290.135    13818164.301
     3192297.948    13818254.578     3192287.531    13818329.231
     3192264.962    13818841.384     3192229.721     13819830.06
     3192207.316    13820249.414     3192161.533    13820783.226
      3192148.87    13820806.117     3192156.175    13820821.703
     3192154.714    13820924.958     3192122.082    13821581.507
     3192116.724    13821921.471      3192077.76    13822805.475
      3192099.19    13822875.611     3192076.786    13822920.907
     3192085.066     13823012.96     3192060.226     13823394.81
     3192064.122    13823592.554     3192042.205    13824120.521
     3192041.718    13824488.734       3192019.8    13824889.093
     3192033.438    13824941.208     3192020.774    13825057.126
     3192000.318     13825640.13     3191991.045    13826303.494

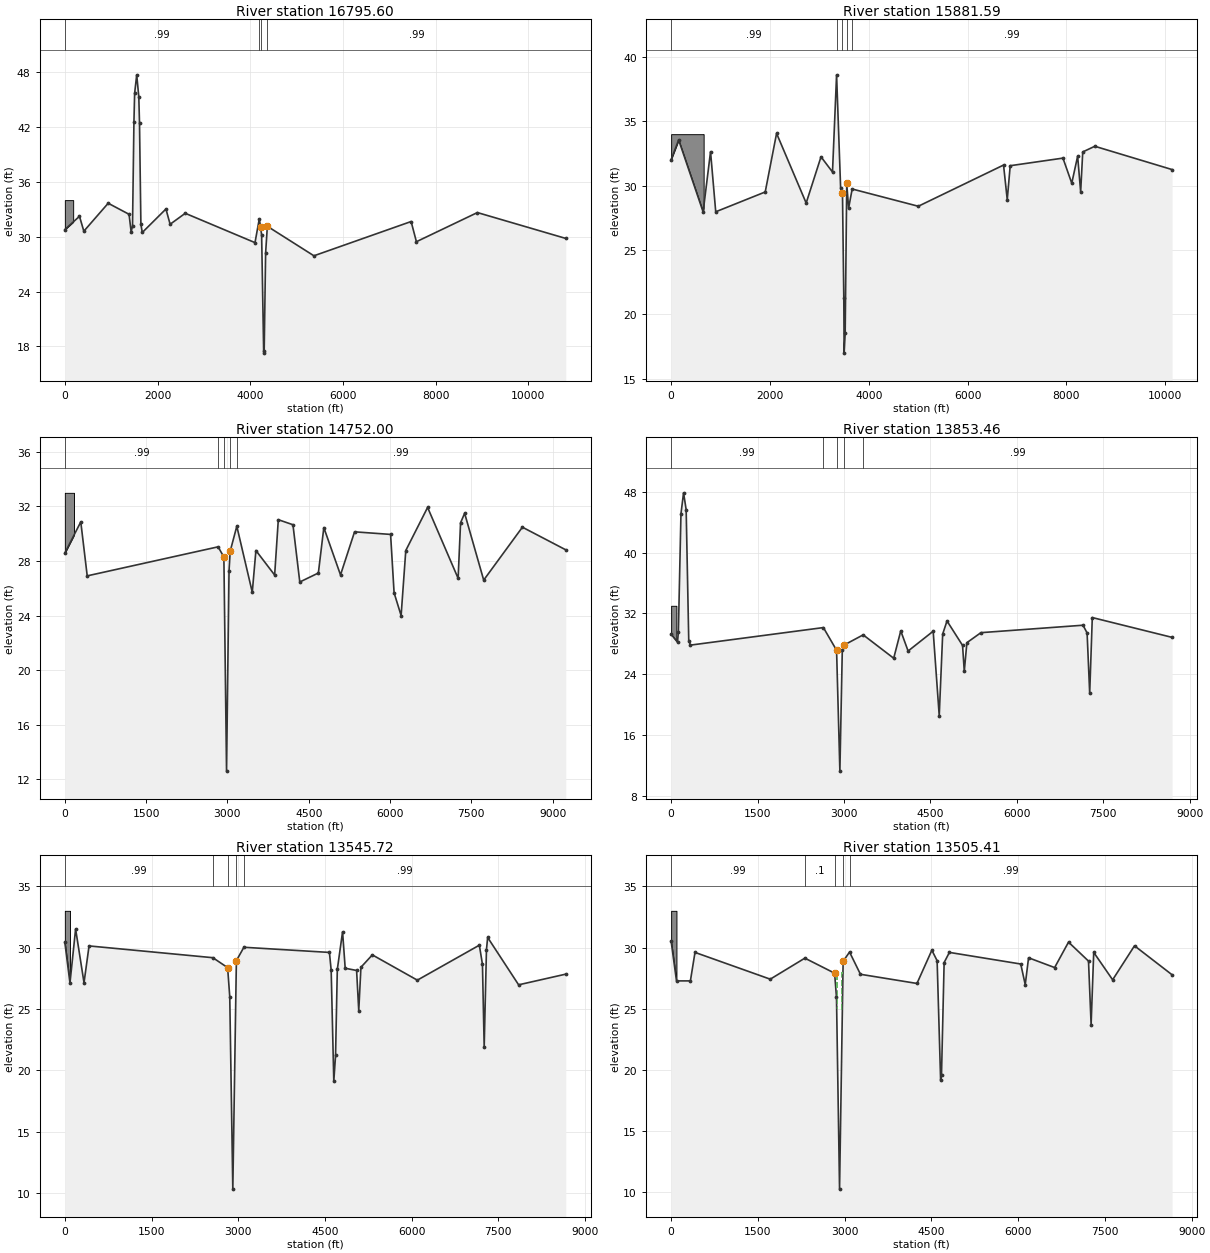
Type RM Length L Ch R = 1 ,16795.60,940.4,914.01,928.18
BEGIN DESCRIPTION:
survey data from sta 4196.55 thru 4392.95; blocked obstructions placed at drainage area boundaries
END DESCRIPTION:
XS GIS Cut Line= 4
      3187955.06    13819160.265     3192143.788    13819346.374
     3192348.585    13819355.279     3198755.281    13819629.376
#Sta/Elev= 30
       0   30.78  316.19   32.23  410.08    30.6   935.6   33.66 1386.04   32.45
 1431.09   30.52 1460.45   31.16 1491.14   42.53 1506.16   45.68  1551.2   47.71
 1596.25   45.29 1611.26   42.47 1641.29   31.36 1671.32   30.46 2181.83   33.03
 2271.91   31.36 2598.49   32.56 4103.72   29.35 4196.55   31.95 4223.14   31.08
 4246.86   30.18 4290.59   17.48 4301.36   17.26 4333.07   28.23 4370.42   31.14
 5375.41   27.91 7473.17   31.66 7586.92   29.45 8902.87   32.6410810.41   29.81
#Mann= 4 ,-1 , 0
       0     .99       0 4196.55      .1       0 4223.14     .04       0
 4370.42     .99       0
#Block Obstruct= 2 , 0
       0     180      34    9922       0      34
Bank Sta=4223.14,4370.42
XS Rating Curve= 0
Exp/Cntr=.3,.1

Type RM Length L Ch R = 1 ,15881.59,1237.65,1129.6,1198.13
BEGIN DESCRIPTION:
survey data from sta 3431.07 thru 3592.84; blocked obstructions placed at drainage area boundaries
END DESCRIPTION:
XS GIS Cut Line= 6
      3188692.26    13820237.334     3190681.232    13820192.958
     3195300.448    13820431.185     3197113.353    13820505.035
     3197673.185    13820431.185     3198819.056    13820483.594
#Sta/Elev= 30
       0   32.03  152.51   33.55  647.64   27.96  797.67   32.64   902.7   27.97
  1904.7   29.51 2134.52   34.06 2733.73   28.65 3034.03   32.24 3266.73   31.06
 3349.35   38.61 3431.07   29.83 3468.71   29.41 3495.56   21.27  3502.3   16.99
 3523.29   18.54 3554.97   30.17 3592.84   28.25 3664.92   29.74 5003.51    28.4
 6729.26    31.6 6804.32   28.91 6864.37   31.55 7931.96   32.14  8110.4   30.19
 8229.31   32.29 8290.56   29.52 8332.58   32.62 8576.94   33.0610141.03   31.25
#Mann= 5 ,-1 , 0
       0     .99       0 3349.35      .1       0 3468.71     .04       0
 3554.97      .1       0 3664.92     .99       0
#Block Obstruct= 2 , 0
       0     658      34    9931       0      34
Bank Sta=3468.71,3554.97
XS Rating Curve= 0
Exp/Cntr=.3,.1

Type RM Length L Ch R = 1 ,14752.00,914.61,898.54,906.15
BEGIN DESCRIPTION:
survey data from sta 2904.49 thru 3051.47; blocked obstructions placed at drainage area boundaries
END DESCRIPTION:
XS GIS Cut Line= 5
      3189151.89    13821430.184     3192050.705    13821383.699
     3192209.916    13821386.284      3195322.71    13821517.613
     3198389.168    13821653.781
#Sta/Elev= 30
       0   28.58  294.19   30.87   412.9   26.91 2828.21   29.04 2934.77   28.29
 2983.95   12.59 3029.86   27.29 3051.47   28.72 3173.34   30.55 3458.59   25.71
 3525.76   28.77  3871.5   26.97 3939.02   31.03 4209.26   30.66 4335.38   26.46
 4678.21   27.12 4779.05   30.45 5086.89   26.98 5346.03   30.14 6010.86   29.95
 6075.55   25.67 6205.13      24 6291.39   28.77 6693.93   31.93 7257.07   26.73
 7302.12    30.8 7377.19    31.5 7729.03    26.6 8443.24   30.48 9243.46   28.82
#Mann= 5 ,-1 , 0
       0     .99       0 2828.21      .1       0 2934.77     .04       0
 3051.47      .1       0 3173.34     .99       0
#Block Obstruct= 2 , 0
       0     169      33    8630       0      33
Bank Sta=2934.77,3051.47
XS Rating Curve= 0
Exp/Cntr=.3,.1

Type RM Length L Ch R = 1 ,13853.46,381.67,307.73,200.65
BEGIN DESCRIPTION:
survey data from sta 2845.95 thru 2997.55; blocked obstructions placed at drainage area boundaries
END DESCRIPTION:
XS GIS Cut Line= 6
     3189199.132    13822286.243     3190463.437     13822328.46
     3190663.969    13822223.835     3194261.923     13822328.46
     3196467.777    13822415.648     3197856.971    13822270.335
#Sta/Elev= 30
       0   29.25  110.66    28.2  125.67   29.58   170.7   45.13  215.72   47.88
  260.75   45.66  305.77    28.4  335.79   27.82 2642.88   30.13  2871.8   27.14
 2929.09   11.22 2970.81   27.14 2997.55   27.81 3333.27   29.17 3863.24   26.09
 3985.82   29.69 4113.44   27.04 4548.54   29.65 4653.56   18.52 4713.57   29.28
 4788.59      31 5058.55   27.78 5088.34   24.37 5133.69   28.14  5377.2   29.46
 7149.42   30.44 7220.31   29.42 7265.35   21.47 7310.44   31.45 8695.19   28.84
#Mann= 5 ,-1 , 0
       0     .99       0 2642.88      .1       0  2871.8     .04       0
 2997.55      .1       0 3333.27     .99       0
#Block Obstruct= 2 , 0
       0      91      33    8584       0      33
Bank Sta=2871.8,2997.55
XS Rating Curve= 0
Exp/Cntr=.3,.1

Type RM Length L Ch R = 1 ,13545.72,41.06,40.31,58.39
BEGIN DESCRIPTION:
structure XS 4, upstream of 13th St. bridge
survey data from sta 2824.30 thru 3014.26; blocked obstructions placed at drainage area boundaries
END DESCRIPTION:
XS GIS Cut Line= 6
     3189190.962    13822644.695     3191256.847    13822563.868
     3193250.544    13822607.462     3194218.329    13822462.148
     3196458.972    13822562.882     3197830.154    13822513.599
#Sta/Elev= 30
       0   30.43   88.82   27.12  186.39   31.52   331.8   27.14   418.9   30.14
 2561.11   29.18 2816.23   28.37 2852.97      26 2905.94   10.32 2967.67   28.94
  3097.6   30.03  4577.1   29.61 4607.44   28.16 4652.94   19.12 4683.28   21.21
 4713.62   28.22 4804.63   31.29 4850.13   28.32 5047.32   28.14 5084.61   24.86
 5122.43    28.4 5319.57   29.41 6098.05   27.35 7170.92    30.2 7224.55   28.64
 7254.58   21.91 7293.85   29.83 7314.63   30.83 7850.17   26.97 8665.92   27.84
#Mann= 5 ,-1 , 0
       0     .99       0 2561.11      .1       0 2816.23     .04       0
 2967.67      .1       0  3097.6     .99       0
#Block Obstruct= 2 , 0
       0      89      33    8576       0      33
Bank Sta=2816.23,2967.67
XS Rating Curve= 0
Exp/Cntr=.5,.3

Type RM Length L Ch R = 1 ,13505.41,95.79,73.74,118.95
BEGIN DESCRIPTION:
structure XS 3, immediately upstream of 13th St. bridge
survey data from sta 2830.04 thru 3020.00; copied from cross-section 13545.72, then adjusted vertically and horizontally; blocked obstructions placed at drainage area boundaries
END DESCRIPTION:
XS GIS Cut Line= 6
     3189186.877    13822694.736     3190582.594    13822738.244
     3191248.128    13822604.476     3193227.294    13822665.587
     3194218.329     13822523.18      3197819.21    13822623.035
#Sta/Elev= 30
       0   30.52    92.9   27.27  333.02   27.27  412.56    29.6 1713.58   27.41
 2311.91   29.13 2826.22    27.9 2858.71   25.92 2911.68   10.24 2973.41   28.87
 3084.34   29.63 3273.11   27.81 4249.85   27.06 4507.47   29.78  4598.4   28.92
 4659.01   19.16 4674.17   19.58 4719.63   28.77 4810.56    29.6 6044.27   28.65
 6121.77   26.96 6179.43   29.16 6629.99   28.36  6870.1   30.44 7215.71   28.89
 7260.76    23.7  7305.8    29.6 7632.94   27.36 8010.82   30.14 8660.31   27.77
#Mann= 5 ,-1 , 0
       0     .99       0 2311.91      .1       0 2826.22     .04       0
 2973.41      .1       0 3084.34     .99       0
#XS Ineff= 2 ,-1
    2823    2862    28.1 2960.19    2970    28.1
Permanent Ineff=
       F       F
#Block Obstruct= 2 , 0
       0      92      33    8572       0      33
Bank Sta=2826.22,2973.41
XS Rating Curve= 0
Exp/Cntr=.5,.3

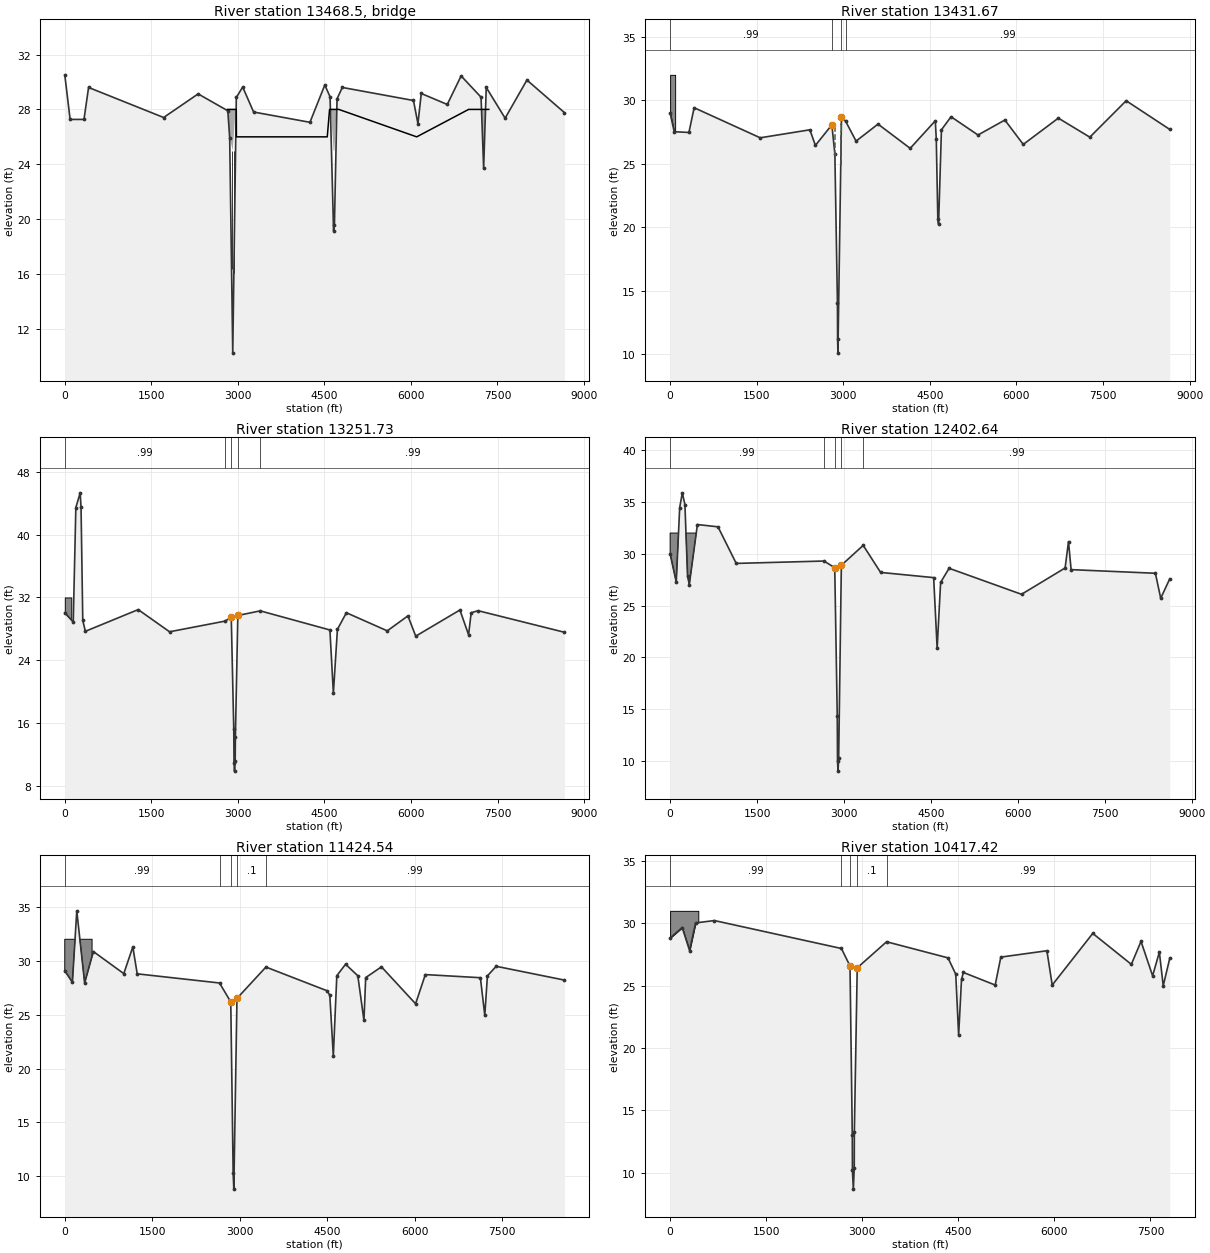
Type RM Length L Ch R = 3 ,13468.5 ,,,
BEGIN DESCRIPTION:
13th St.
END DESCRIPTION:
Bridge Culvert--1,0,-1,-1, 0
Deck Dist Width WeirC Skew NumUp NumDn MinLoCord MaxHiCord MaxSubmerge Is_Ogee
9.5,54,2.6,0, 10, 6, , , .95, 0, 2,2,,
    2820    2823    2973    2975    4550    4590    4750    6100    7000    7350
      28      28      28      26      26      28      28      26      28      28
      25      25      25      23      23      25      25      23      23      23
    2802    2968    2970    4550    4590    4730
      28      28      26      26      28      28
      25      25      23      23      25      25
Pier Skew, UpSta & Num, DnSta & Num=  ,2891, 2 ,2888, 2 , 0 , 0 , 0 ,,
     1.2     1.2
      11      26
     1.2     1.2
      11      26
Pier Skew, UpSta & Num, DnSta & Num=  ,2931, 2 ,2928, 2 , 0 , 0 , 0 ,,
     1.2     1.2
      11      26
     1.2     1.2
      11      26
BR Coef=-1 , 1 , 1 ,1.25, 0 ,,,.8,-1,2,0,
WSPro=,,,, 1 ,,,, 0 ,,,, 0 ,,,,-1 ,-1 ,-1 , 0 , 0 , 0 , 0 , 0
BC Design=,, 0 ,, 0 ,,,,,,
BC HTab HWMax=30.52

Type RM Length L Ch R = 1 ,13431.67,183.88,179.95,224.72
BEGIN DESCRIPTION:
structure XS 2, immediately downstream of 13th St. bridge survey data from sta 2825.23 thru 3015.19; copied from cross-section 13545.72, then adjusted vertically and horizontally; blocked obstructions placed at drainage area boundaries
END DESCRIPTION:
XS GIS Cut Line= 6
     3189194.026    13822809.114     3190536.094    13822842.869
     3191320.785    13822685.931     3193267.981    13822776.025
     3194189.267    13822648.149      3197819.19    13822749.869
#Sta/Elev= 30
       0   28.99   70.73   27.52  325.81   27.46  415.84   29.41 1560.36   27.04
 2420.81   27.67 2516.74   26.44 2801.79   28.06  2853.9   25.76 2898.35      14
 2901.23   11.21 2906.87   10.08  2968.6   28.71 3042.04   28.33  3221.2   26.78
 3601.53   28.12 4158.63   26.21 4593.94   28.38 4610.77   26.92 4637.36   20.63
 4650.66   20.23 4699.94   27.67 4866.53    28.7 5333.35   27.26 5798.87   28.44
  6117.6   26.52 6725.14   28.59 7270.51   27.09 7900.22   29.96  8655.1    27.7
#Mann= 4 ,-1 , 0
       0     .99       0 2801.79     .04       0  2968.6      .1       0
 3042.04     .99       0
#XS Ineff= 2 ,-1
    2805 2856.72    28.1    2956    2966    28.1
Permanent Ineff=
       F       F
#Block Obstruct= 2 , 0
       0      87      32    8563       0      32
Bank Sta=2801.79,2968.6
XS Rating Curve= 0
Exp/Cntr=.5,.3

Type RM Length L Ch R = 1 ,13251.73,872.25,849.09,858.95
BEGIN DESCRIPTION:
structure XS 1, downstream of 13th St. bridge
survey data from sta 2847.76 thru 3034.65; copied from cross-section 12402.64, then adjusted vertically and horizontally; blocked obstructions placed at drainage area boundaries
END DESCRIPTION:
XS GIS Cut Line= 6
     3189162.834    13822930.153      3190562.25     13822959.12
     3192003.757    13822875.359     3193343.284    13822951.343
     3194229.714    13822896.625     3197808.266    13823060.779
#Sta/Elev= 30
       0   30.04  146.93   28.86  191.94   43.47  266.96   45.35  281.96    43.5
  311.97   29.07  356.98   27.68 1272.17   30.45 1815.95   27.62 2776.53   28.98
 2885.12   29.47 2928.39   15.18 2932.92   10.86 2941.59    9.84 2953.03   11.13
 2956.42   14.18 2999.01    29.7 3387.46   30.29 4594.51   27.85 4654.63   19.77
 4724.61   27.93 4880.05   30.05 5588.61   27.74  5946.4   29.65 6081.55   27.06
 6847.41    30.4 6997.58   27.24 7042.63   30.05 7162.77   30.31 8657.73   27.56
#Mann= 5 ,-1 , 0
       0     .99       0 2776.53      .1       0 2885.12     .04       0
 2999.01      .1       0 3387.46     .99       0
#Block Obstruct= 2 , 0
       0     113      32    8566       0      32
Bank Sta=2885.12,2999.01
XS Rating Curve= 0
Exp/Cntr=.3,.1

Type RM Length L Ch R = 1 ,12402.64,989.1,978.1,928.32
BEGIN DESCRIPTION:
survey data from sta 2803.10 thru 2989.99; blocked obstructions placed at drainage area boundaries
END DESCRIPTION:
XS GIS Cut Line= 4
     3189159.186    13823773.414     3191904.621     13823713.06
     3192223.621    13823722.801     3197775.436    13823925.322
#Sta/Elev= 30
       0      30  105.57   27.28  165.02   34.46   210.6   35.88  255.32   34.74
  300.62   27.88  330.63   27.02  470.68   32.82  825.75    32.6 1140.82   29.07
 2656.19    29.3 2840.46   28.65 2883.73   14.37 2888.26   10.05 2896.93    9.03
 2908.37   10.32 2954.35   28.89 3331.54   30.81 3631.74    28.2 4547.35    27.7
 4607.39   20.89 4667.43   27.24 4813.67    28.6 6063.35   26.09 6815.27   28.63
 6873.89   31.18 6918.92   28.47 8373.09   28.12 8464.95   25.71 8620.75   27.58
#Mann= 5 ,-1 , 0
       0     .99       0 2656.19      .1       0 2840.46     .04       0
 2954.35      .1       0 3331.54     .99       0
#Block Obstruct= 2 , 0
       0     470      32    8519       0      32
Bank Sta=2840.46,2954.35
XS Rating Curve= 0
Exp/Cntr=.3,.1

Type RM Length L Ch R = 1 ,11424.54,1000.66,1007.12,1004.82
BEGIN DESCRIPTION:
survey data from sta 2813.81 thru 2988.59; blocked obstructions placed at drainage area boundaries
END DESCRIPTION:
XS GIS Cut Line= 5
     3189134.172    13824790.647       3191875.4    13824689.539
     3192201.705     13824699.28     3194774.809    13824711.436
     3197693.098     13824819.83
#Sta/Elev= 30
       0   29.08  130.65      28   205.7   34.64  340.79   27.94  490.38   30.86
 1011.52   28.81 1166.36   31.29 1241.41   28.79 2652.37   27.94 2845.07   26.18
 2886.02   10.26  2897.4     8.8 2951.31   26.51 3447.58   29.42 4494.05   27.22
 4542.59    26.8 4602.59   21.14 4662.59   28.62 4812.59   29.68 5022.59   28.61
  5127.6   24.46  5157.6   28.44  5427.6   29.44 6012.86   26.01 6179.61   28.72
 7123.62   28.43 7198.67   24.93 7243.71    28.6 7393.81   29.49 8562.98   28.21
#Mann= 5 ,-1 , 0
       0     .99       0 2652.37      .1       0 2845.07     .04       0
 2951.31      .1       0 3447.58     .99       0
#Block Obstruct= 2 , 0
       0     468      32    7602       0      32
Bank Sta=2845.07,2951.31
XS Rating Curve= 0
Exp/Cntr=.3,.1

Type RM Length L Ch R = 1 ,10417.42,591.23,588.52,586.92
BEGIN DESCRIPTION:
survey data from sta 2808.47 thru 2965.62; blocked obstructions placed at drainage area boundaries
END DESCRIPTION:
XS GIS Cut Line= 6
     3189140.947    13825752.901     3191892.446    13825692.805
     3192150.567    13825702.545     3193936.846    13825701.379
     3194708.105    13825620.275     3196926.005    13825837.062
#Sta/Elev= 30
       0   28.82   188.6   29.66  303.86   27.81  397.76   30.03   691.6   30.22
 2674.42   27.98 2808.47   26.58 2844.06   13.06 2846.26   10.19 2860.81    8.69
 2874.72   10.39 2876.46   13.27 2921.34   26.43 3379.63   28.52 4338.21   27.23
 4459.63   25.92 4504.63   21.02 4549.63   25.52 4578.84   26.06 5075.31   25.05
 5163.29   27.29 5882.95    27.8 5965.75   25.05 6598.75   29.19 7200.98   26.71
 7352.32   28.55 7533.18   25.79 7638.68   27.69 7698.96   24.99 7800.72   27.19
#Mann= 5 ,-1 , 0
       0     .99       0 2674.42      .1       0 2808.47     .04       0
 2921.34      .1       0 3379.63     .99       0
#Block Obstruct= 2 , 0
       0     440      31    7552       0      31
Bank Sta=2808.47,2921.34
XS Rating Curve= 0
Exp/Cntr=.3,.1

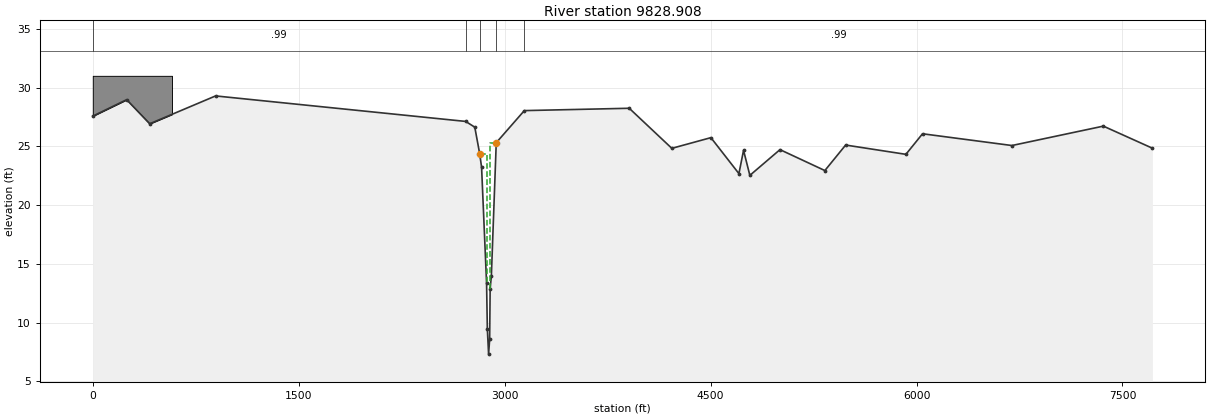
Type RM Length L Ch R = 1 ,9828.908,,,
BEGIN DESCRIPTION:
end of channel, entrance to culvert under SH 225 and Shell plant
survey data from sta 2799.60 thru 2999.28; blocked obstructions placed at drainage area boundaries
END DESCRIPTION:
XS GIS Cut Line= 6
     3189108.116    13826278.193     3190355.685    13826316.495
     3193594.986    13826291.481     3194120.278    13826087.201
     3194374.586    13826037.173     3196759.246    13826345.678
#Sta/Elev= 30
       0   27.57  246.74   28.97  414.64   26.92  894.59   29.29 2716.41   27.12
 2782.56   26.63 2818.92   24.33  2832.1   23.21 2868.44   13.35 2873.91    9.49
 2883.12    7.32 2890.75    8.57 2894.45   12.88 2903.22   13.95  2938.9   25.31
 3143.36   28.04 3907.57   28.24  4217.8   24.83 4502.35   25.74 4706.46   22.68
 4740.14   24.66 4786.12   22.53 5005.61   24.72 5332.44   22.94  5483.8   25.11
 5922.75   24.32 6043.83   26.07 6694.86   25.07 7361.06   26.72 7718.43   24.84
#Mann= 5 ,-1 , 0
       0     .99       0 2716.41      .1       0 2818.92     .04       0
  2938.9      .1       0 3143.36     .99       0
#XS Ineff= 2 ,-1
 2818.92 2868.44   24.33 2894.45  2938.9   25.31
Permanent Ineff=
       T       T
#Block Obstruct= 2 , 0
       0     577      31    7597       0      31
Bank Sta=2818.92,2938.9
XS Rating Curve= 0
Exp/Cntr=.3,.1

Chan Stop Cuts=-1